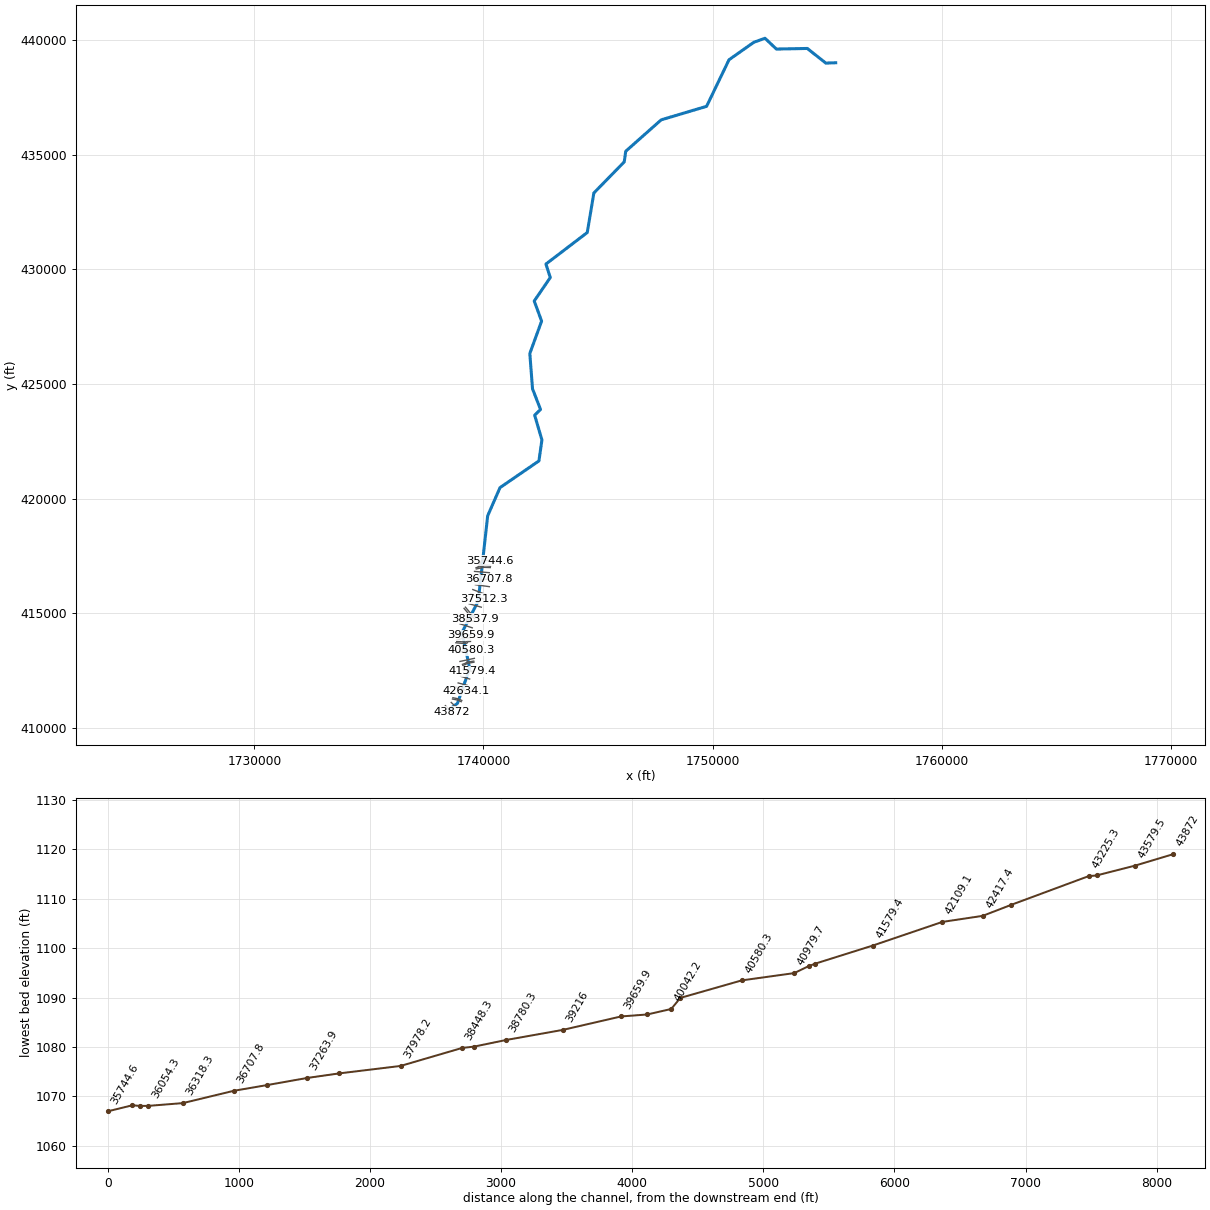
--- RFkMrcleRn.prj (project) ---

Proj Title=RFkMrcleRn
Current Plan=p01
Default Exp/Contr=0,0
English Units
Geom File=g01
Flow File=f01
Plan File=p01
BEGIN DESCRIPTION:
END DESCRIPTION:
DSS Export Rating Curves= 0
DSS Export Rating Curve Sorted= 0
DSS Export Volume Flow Curves= 0
DXF OffsetX= 0
DXF OffsetY= 0
DXF ScaleX= 0
DXF ScaleY= 0

--- RFkMrcleRn.p01 (plan) ---

Plan Title=Floodplain
Program Version=4.00
Geom File=g01
Flow File=f01
K Sum by GR=0
Std Step Tol=0.01
Critical Tol=0.01
Num of Std Step Trials=20
Max Error Tol=0.3
Flow Tol Ratio=0.001
Split Flow NTrial=30
Split Flow Tol=0.02
Split Flow Ratio=0.02
Log Output Level=0
Friction Slope Method=1
Unsteady Friction Slope Method=2
Unsteady Bridges Friction Slope Method=1
Global Log Level=0
CheckData=False
Run HTab=0
Run UNet=0
Run PostProcess=0
UNET Theta=0
UNET Theta Warmup=0
UNET ZTol=0
UNET ZSATol=0
UNET MxIter=0
UNET MaxInSteps=0
UNET DtIC=0
UNET DtMin=0
UNET MaxCRTS=0
UNET WFStab=0
UNET SFStab=0
UNET WFX=0
UNET SFX=0
UNET DSS MLevel=0
UNET DZMax Abort=0
UNET Convert EG Bridges=0
UNET Use Existing IB Tables=0
UNET Froude Limit=0
UNET Froude Power=0
Write IC File=0
Echo Input=False
Echo Output=False
Write Detailed=0

--- RFkMrcleRn.f01 (steady flow) ---

Flow Title=NFF Regression Equation
Program Version=4.00
Number of Profiles=1
Profile Names=P100yr
River Rch & RM=RFkMrcleRn,Main      ,43872
     957
River Rch & RM=RFkMrcleRn,Main      ,38537.9
     966
River Rch & RM=RFkMrcleRn,Main      ,36958.6
    1046
River Rch & RM=RFkMrcleRn,Main      ,34153.6
    1130
River Rch & RM=RFkMrcleRn,Main      ,33776.9
    1259
River Rch & RM=RFkMrcleRn,Main      ,32380.5
    1282
River Rch & RM=RFkMrcleRn,Main      ,30254.8
    1348
River Rch & RM=RFkMrcleRn,Main      ,29713.8
    1679
River Rch & RM=RFkMrcleRn,Main      ,28927.6
    1711
River Rch & RM=RFkMrcleRn,Main      ,27019.2
    1786
River Rch & RM=RFkMrcleRn,Main      ,24268.7
    1909
River Rch & RM=RFkMrcleRn,Main      ,21670.3
    2024
River Rch & RM=RFkMrcleRn,Main      ,19277
    2074
River Rch & RM=RFkMrcleRn,Main      ,18994.8
    2277
River Rch & RM=RFkMrcleRn,Main      ,17657.8
    2316
River Rch & RM=RFkMrcleRn,Main      ,16334.7
    2336
River Rch & RM=RFkMrcleRn,Main      ,13429.6
    2439
River Rch & RM=RFkMrcleRn,Main      ,12458.1
    2447
River Rch & RM=RFkMrcleRn,Main      ,11689.9
    2508
River Rch & RM=RFkMrcleRn,Main      ,8562.6
    2600
River Rch & RM=RFkMrcleRn,Main      ,5710.9
    2684
River Rch & RM=RFkMrcleRn,Main      ,5202.3
    2728
River Rch & RM=RFkMrcleRn,Main      ,4632.5
    2733
River Rch & RM=RFkMrcleRn,Main      ,1957.9
    2786
River Rch & RM=RFkMrcleRn,Main      ,180
    2851
Boundary for River Rch & Prof#=RFkMrcleRn,Main      ,1
Up Type=0
Dn Type=3
Dn Slope=0.003157

--- RFkMrcleRn.g01 (geometry) ---

Geom Title=USGS 10m DEM
Program Version=4.10

River Reach=RFkMrcleRn      ,Main
Reach XY= 30
     1738510.504      410795.593     1738866.017      411056.953
     1739399.632      412587.053     1739066.661      414160.265
     1739771.477      415519.198     1740184.674      419246.665
     1740723.367      420476.065     1742421.284      421640.995
     1742551.492      422557.662      1742235.52      423637.523
     1742490.728      423887.523      1742141.18      424790.919
     1742024.362       426331.88       1742538.9      427743.725
     1742216.118      428619.858     1742917.313      429644.928
     1742726.837      430233.966      1744530.16      431610.206
     1744818.355        433335.9     1746144.534      434693.287
      1746208.98      435157.081     1747757.591      436528.609
     1749738.494      437118.887      1750717.66      439151.873
     1751799.257      439914.025      1752288.02      440089.858
     1752784.434      439618.143     1754134.327      439644.928
     1754942.776      439004.882      1755373.05      439021.013

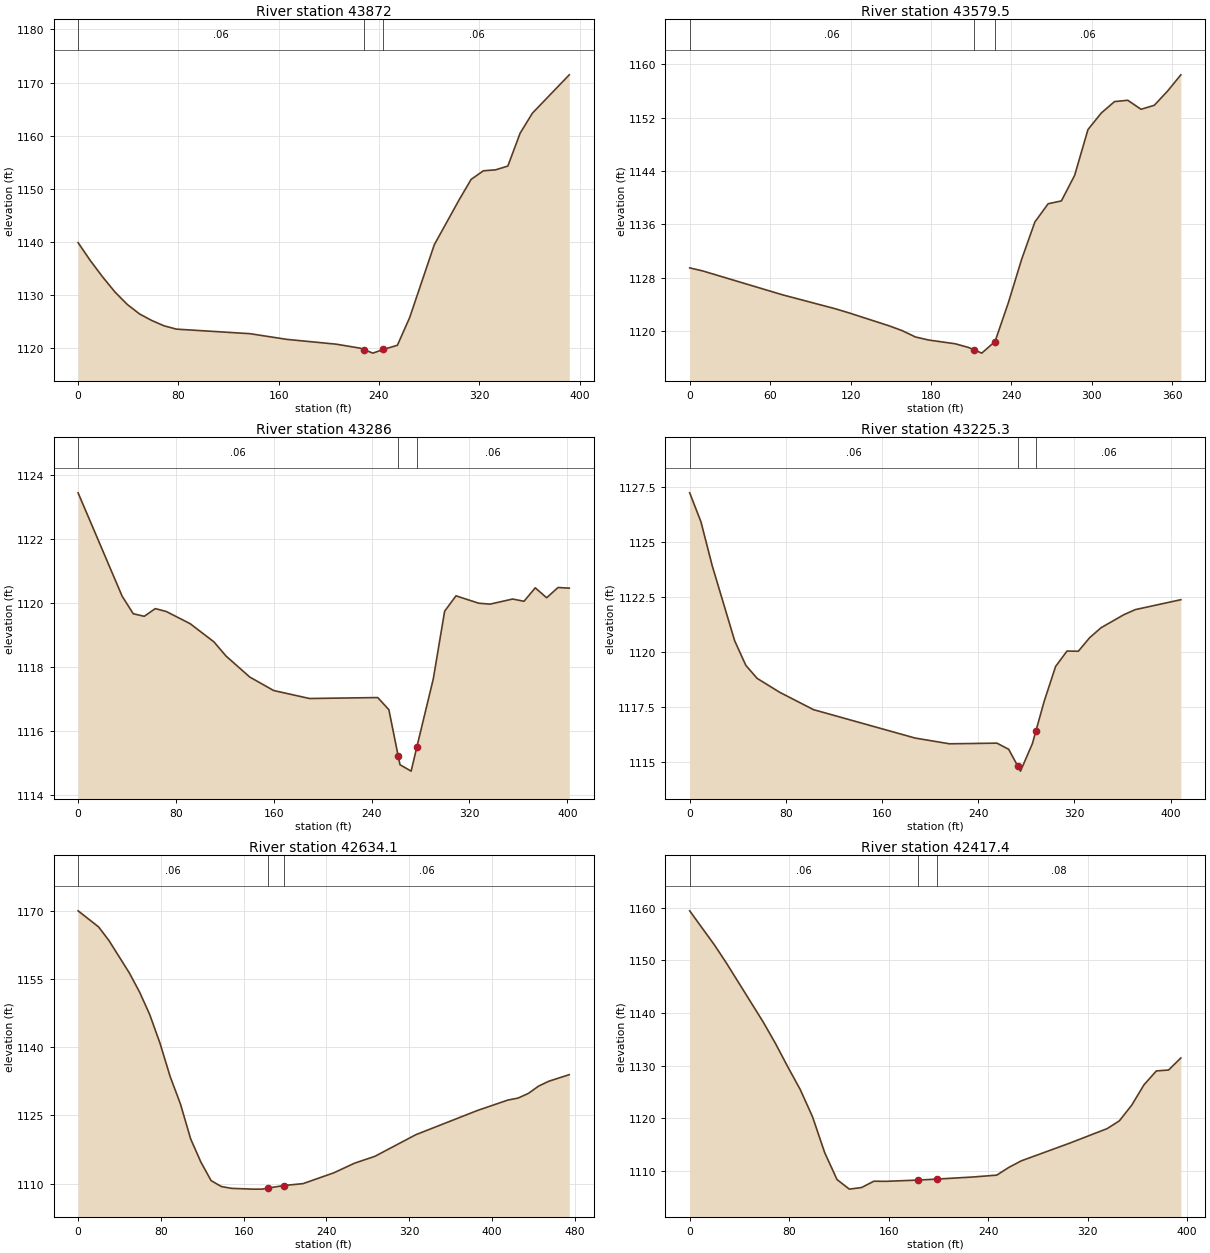
Type RM Length L Ch R = 1 ,43872   ,291.4,292.4,292.4
XS GIS Cut Line= 2
     1738339.116      410958.175     1738625.252      410690.488
#Sta/Elev= 27
       0 1139.86     9.8 1136.47    19.6  1133.4    29.4 1130.57    39.2 1128.23
      49 1126.44    58.8  1125.2    68.6  1124.2    78.4 1123.58   137.1 1122.72
   166.5 1121.65   205.7 1120.75   225.3 1119.98   228.4 1119.69   235.1 1119.06
   243.6 1119.76   254.7 1120.54   264.5 1125.76   284.1 1139.45   303.7 1147.82
   313.5 1151.77   323.3 1153.39     333 1153.57   342.8 1154.28   352.6 1160.47
   362.4 1164.24   391.8 1171.46
#Mann= 3 , 0 , 0
       0     .06       0   228.4    .045       0   243.6     .06       0
Bank Sta=228.4,243.6
XS Rating Curve= 0 ,0
Exp/Cntr=0.3,0.1

Type RM Length L Ch R = 1 ,43579.5 ,284.2,293.6,302.6
XS GIS Cut Line= 2
     1738593.227      411099.113     1738860.816      410848.777
#Sta/Elev= 29
       0  1129.5     9.9 1129.03    69.3 1125.46   108.9 1123.36   118.8 1122.76
   148.6 1120.83   158.5  1120.1   168.4 1119.15   178.3 1118.69   198.1 1118.13
     208 1117.58   212.1 1117.23   217.9 1116.73   227.4 1118.41   227.8 1118.48
   237.7 1124.27   247.6 1130.76   257.5 1136.37   267.4  1139.1   277.3 1139.53
   287.2 1143.37   297.1 1150.21     307 1152.68   316.9  1154.4   326.8  1154.6
   336.7 1153.25   346.6 1153.85   356.5 1155.98   366.4 1158.41
#Mann= 3 , 0 , 0
       0     .06       0   212.1    .045       0   227.4     .06       0
Bank Sta=212.1,227.4
XS Rating Curve= 0 ,0
Exp/Cntr=0.3,0.1

Type RM Length L Ch R = 1 ,43286   ,60.7,60.7,60.1
XS GIS Cut Line= 5
     1738648.063      411248.747     1738718.675       411234.15
     1738852.402      411206.504     1738929.234      411178.522
      1739030.28      411132.101
#Sta/Elev= 29
       0 1123.44      36 1120.21    45.1 1119.66    54.1 1119.58    63.1 1119.82
    72.1 1119.73    91.6 1119.35   111.1 1118.78   120.9 1118.34   140.4 1117.68
   159.9 1117.26   189.2 1117.01     245 1117.04   254.1 1116.66   261.8  1115.2
   263.2 1114.94   272.3 1114.74     277  1115.5   290.4 1117.62   299.7 1119.74
     309 1120.22   327.5 1119.99   336.8 1119.96   355.3 1120.12   364.6 1120.05
   373.8 1120.47   383.1 1120.16   392.4 1120.48   401.6 1120.46
#Mann= 3 , 0 , 0
       0     .06       0   261.8    .045       0     277     .06       0
Bank Sta=261.8,277
XS Rating Curve= 0 ,0
Exp/Cntr=0.3,0.1

Type RM Length L Ch R = 1 ,43225.3 ,590.6,591.2,592.3
XS GIS Cut Line= 5
     1738666.753      411306.152     1738730.822      411292.907
     1738868.829      411264.377     1738952.062      411234.064
     1739055.328      411186.623
#Sta/Elev= 25
       0 1127.23     9.4 1125.91    18.7 1123.93    37.4 1120.52    46.7  1119.4
    56.1 1118.81    74.8 1118.18     103 1117.39   187.6  1116.1   216.2 1115.84
   255.6 1115.87   265.4 1115.59   272.9 1114.83   275.2  1114.6   285.1 1115.85
   288.1 1116.44   294.9 1117.77   304.4 1119.35   313.9 1120.05   323.3 1120.04
   332.8 1120.66   342.3 1121.11   361.2  1121.7   370.7 1121.93   408.6 1122.38
#Mann= 3 , 0 , 0
       0     .06       0   272.9    .045       0   288.1     .06       0
Bank Sta=272.9,288.1
XS Rating Curve= 0 ,0
Exp/Cntr=0.3,0.1

Type RM Length L Ch R = 1 ,42634.1 ,214.7,216.7,219.1
XS GIS Cut Line= 2
     1738794.184      411781.627     1739240.122      411618.623
#Sta/Elev= 30
       0 1170.07    19.8 1166.53    29.7 1163.57    49.5 1156.41    59.4 1152.19
    69.2 1147.25    79.1 1140.97      89 1133.57    98.9 1127.56   108.8 1119.85
   118.7 1114.74   128.6 1110.65   138.5 1109.35   148.4 1108.95   168.2 1108.78
     178 1108.78   183.8 1109.03     199 1109.57   217.6    1110   247.3 1112.38
   267.1 1114.48   286.9    1116   326.4 1120.76   385.8 1126.08   415.4 1128.39
   425.3 1128.83   435.2 1129.85   445.1 1131.46     455 1132.54   474.8 1133.99
#Mann= 3 , 0 , 0
       0     .06       0   183.8    .045       0     199     .06       0
Bank Sta=183.8,199
XS Rating Curve= 0 ,0
Exp/Cntr=0.3,0.1

Type RM Length L Ch R = 1 ,42417.4 ,309,308.3,316.2
XS GIS Cut Line= 2
     1738896.785      411950.446     1739279.117      411851.185
#Sta/Elev= 28
       0 1159.37    19.8 1152.93    29.6 1149.44    59.2 1138.24    69.1 1134.15
      79 1129.72    88.9 1125.46    98.8 1120.28   108.6 1113.47   118.5 1108.37
   128.4 1106.56   138.2 1106.86   148.1 1108.06     158 1108.04     184 1108.28
   199.2 1108.47   227.1 1108.85   246.9 1109.21   256.8  1110.7   266.6 1111.92
   306.1 1115.33   335.8 1118.05   345.6 1119.53   355.5  1122.5   365.4 1126.37
   375.3 1128.99   385.1 1129.16     395 1131.45
#Mann= 3 , 0 , 0
       0     .06       0     184    .045       0   199.2     .08       0
Bank Sta=184,199.2
XS Rating Curve= 0 ,0
Exp/Cntr=0.3,0.1

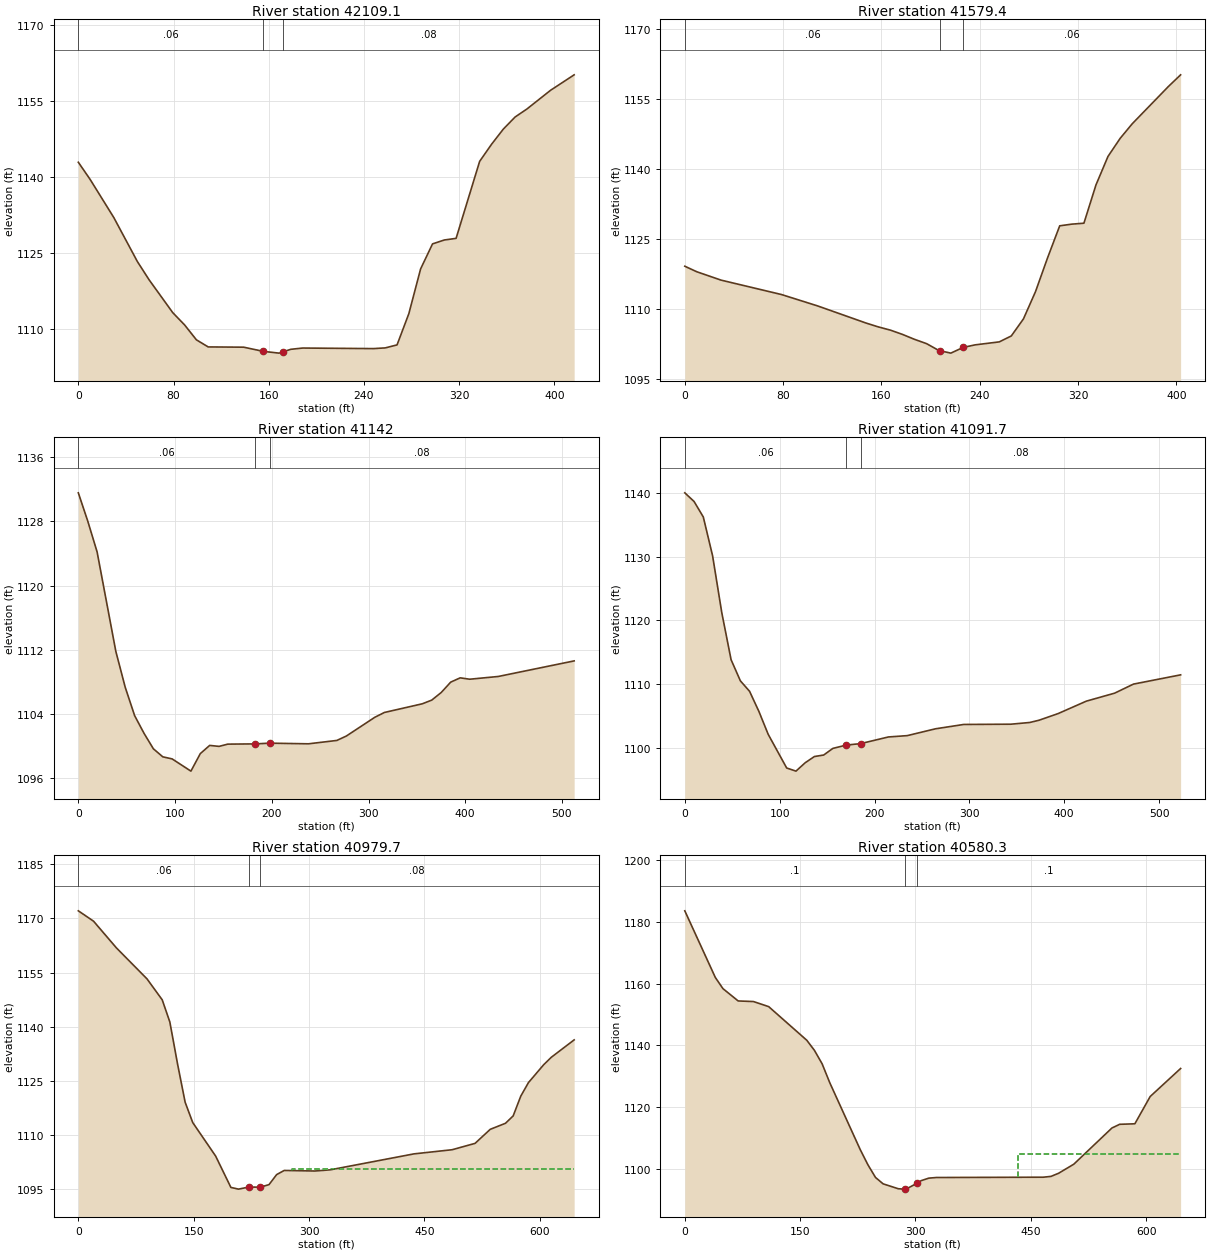
Type RM Length L Ch R = 1 ,42109.1 ,503.1,529.7,452.7
XS GIS Cut Line= 2
     1738999.407      412243.337     1739397.949      412122.027
#Sta/Elev= 30
       0  1142.9     9.9 1139.53    29.8 1132.02    49.6 1123.36    59.5 1119.75
    79.4 1113.28    89.3 1110.88    99.2 1107.95   109.1 1106.55   138.9  1106.5
   155.4 1105.68   168.6 1105.33   171.9 1105.58   178.5 1106.08   188.5 1106.33
     248 1106.22   257.9 1106.36   267.8 1106.95   277.7  1113.1   287.6 1121.91
   297.6 1126.83   307.5  1127.6   317.4 1127.92   337.2 1143.08   347.2 1146.44
   357.1 1149.43     367 1151.81   376.9 1153.38   396.8 1157.07   416.6 1160.11
#Mann= 3 , 0 , 0
       0     .06       0   155.4    .045       0   171.9     .08       0
Bank Sta=155.4,171.9
XS Rating Curve= 0 ,0
Exp/Cntr=0.3,0.1

Type RM Length L Ch R = 1 ,41579.4 ,360.6,437.4,424.6
XS GIS Cut Line= 2
     1739107.642      412533.062      1739503.67      412455.828
#Sta/Elev= 30
       0 1119.18     9.8 1117.99    29.5  1116.2    78.7 1113.11   108.2 1110.66
   147.6 1106.99   157.5 1106.17   167.3 1105.48   177.1 1104.57     187  1103.5
   196.8 1102.58   206.7 1101.12   207.7 1101.06   216.5 1100.55   226.5 1101.77
   236.2 1102.32   255.9 1102.96   265.7 1104.23   275.6 1107.89   285.4 1113.73
   295.2 1120.96   305.1 1127.84   314.9  1128.2   324.8  1128.4   334.6  1136.6
   344.4 1142.72   354.3 1146.59   364.1 1149.71   393.6 1157.72   403.5 1160.21
#Mann= 3 , 0 , 0
       0     .06       0   207.7    .045       0   226.5     .06       0
Bank Sta=207.7,226.5
XS Rating Curve= 0 ,0
Exp/Cntr=0.3,0.1

Type RM Length L Ch R = 1 ,41142   ,50.3,50.3,52.4
XS GIS Cut Line= 4
     1739100.627       412714.89     1739237.151      412765.247
     1739285.135      412805.929     1739585.353      412854.728
#Sta/Elev= 30
       0 1131.54     9.7 1128.04    19.4 1124.19    38.8 1111.79    48.5 1107.33
    58.2 1103.81    67.9 1101.61    77.6 1099.68    87.3 1098.68      97 1098.42
   116.4  1096.9   126.1 1099.08   135.8  1100.1   145.5 1099.98   154.5 1100.26
   182.8 1100.29   197.9 1100.38   237.9  1100.3   267.3 1100.72   277.1 1101.27
   306.5  1103.6   316.4  1104.2   355.6 1105.28   365.4 1105.74   375.2 1106.69
     385 1107.98   394.8 1108.51   404.6 1108.34   434.1 1108.68   512.6 1110.62
#Mann= 3 , 0 , 0
       0     .06       0   182.8    .045       0   197.9     .08       0
Bank Sta=182.8,197.9
XS Rating Curve= 0 ,0
Exp/Cntr=0.3,0.1

Type RM Length L Ch R = 1 ,41091.7 ,123.2,112.1,101
XS GIS Cut Line= 4
     1739083.324        412761.8     1739211.557      412809.099
     1739263.399      412853.052     1739577.331       412904.08
#Sta/Elev= 30
       0 1139.99     9.8 1138.63    19.5 1136.21    29.3 1130.13      39 1121.21
    48.8 1113.85    58.6 1110.54    68.3  1108.9    78.1 1105.76    87.9 1102.17
   107.4 1096.89   117.2  1096.4   126.9 1097.71   136.7 1098.69   146.4 1098.92
   156.1 1099.96   170.3 1100.48   185.4 1100.71   214.6 1101.75   234.5 1101.96
   264.3 1103.03   294.1 1103.71   343.8 1103.75   363.7 1104.02   373.6 1104.38
   393.5 1105.41   423.3 1107.36   453.1 1108.61     473 1110.03   522.7 1111.48
#Mann= 3 , 0 , 0
       0     .06       0   170.3    .045       0   185.4     .08       0
Bank Sta=170.3,185.4
XS Rating Curve= 0 ,0
Exp/Cntr=0.3,0.1

Type RM Length L Ch R = 1 ,40979.7 ,400.7,399.4,398.3
XS GIS Cut Line= 2
      1738973.56      412888.203     1739603.869      413024.262
#Sta/Elev= 30
       0 1172.11    19.8 1169.24    49.6 1161.82    89.3 1153.25   109.1 1147.44
     119 1141.31     129  1129.7   138.9 1119.06   148.8 1113.41   178.6 1104.12
   198.4 1095.44   208.3 1094.97   221.7 1095.54   236.8 1095.52     248 1096.22
   257.9    1099   267.8 1100.15   307.5 1099.99   327.4 1100.31   436.5 1104.74
   486.1 1105.89   515.9 1107.65   535.7 1111.55   555.5 1113.22   565.5 1115.27
   575.4 1120.75   585.3 1124.48   605.2 1129.46   615.1 1131.52   644.8 1136.34
#Mann= 3 , 0 , 0
       0     .06       0   221.7    .045       0   236.8     .08       0
#XS Ineff= 2 , 0
                          277.71         1100.42
Permanent Ineff=
       F       F
Bank Sta=221.7,236.8
XS Rating Curve= 0 ,0
Exp/Cntr=0.3,0.1

Type RM Length L Ch R = 1 ,40580.3 ,443.9,468.4,428.7
XS GIS Cut Line= 2
     1738819.368      413277.194     1739456.052      413379.349
#Sta/Elev= 30
       0 1183.54    39.7 1161.98    49.6 1158.37    69.4 1154.38    89.3 1154.19
   109.1 1152.54   158.7 1141.65   168.6 1138.39   178.6 1134.04   188.5 1127.94
   228.2 1106.26   238.1  1101.4     248 1097.28   257.9 1095.21   277.8 1093.61
   286.7 1093.51   287.7  1093.5   301.7 1095.36   307.5 1096.25   317.4 1097.06
   327.4 1097.26   466.3 1097.36   476.2 1097.62   486.1 1098.63   505.9 1101.57
   555.5 1113.28   565.5 1114.47   585.3 1114.64   605.2 1123.46   644.8 1132.53
#Mann= 3 , 0 , 0
       0      .1       0   286.7    .045       0   301.7      .1       0
#XS Ineff= 2 , 0
                          433.39         1104.84
Permanent Ineff=
       F       F
Bank Sta=286.7,301.7
XS Rating Curve= 0 ,0
Exp/Cntr=0.3,0.1

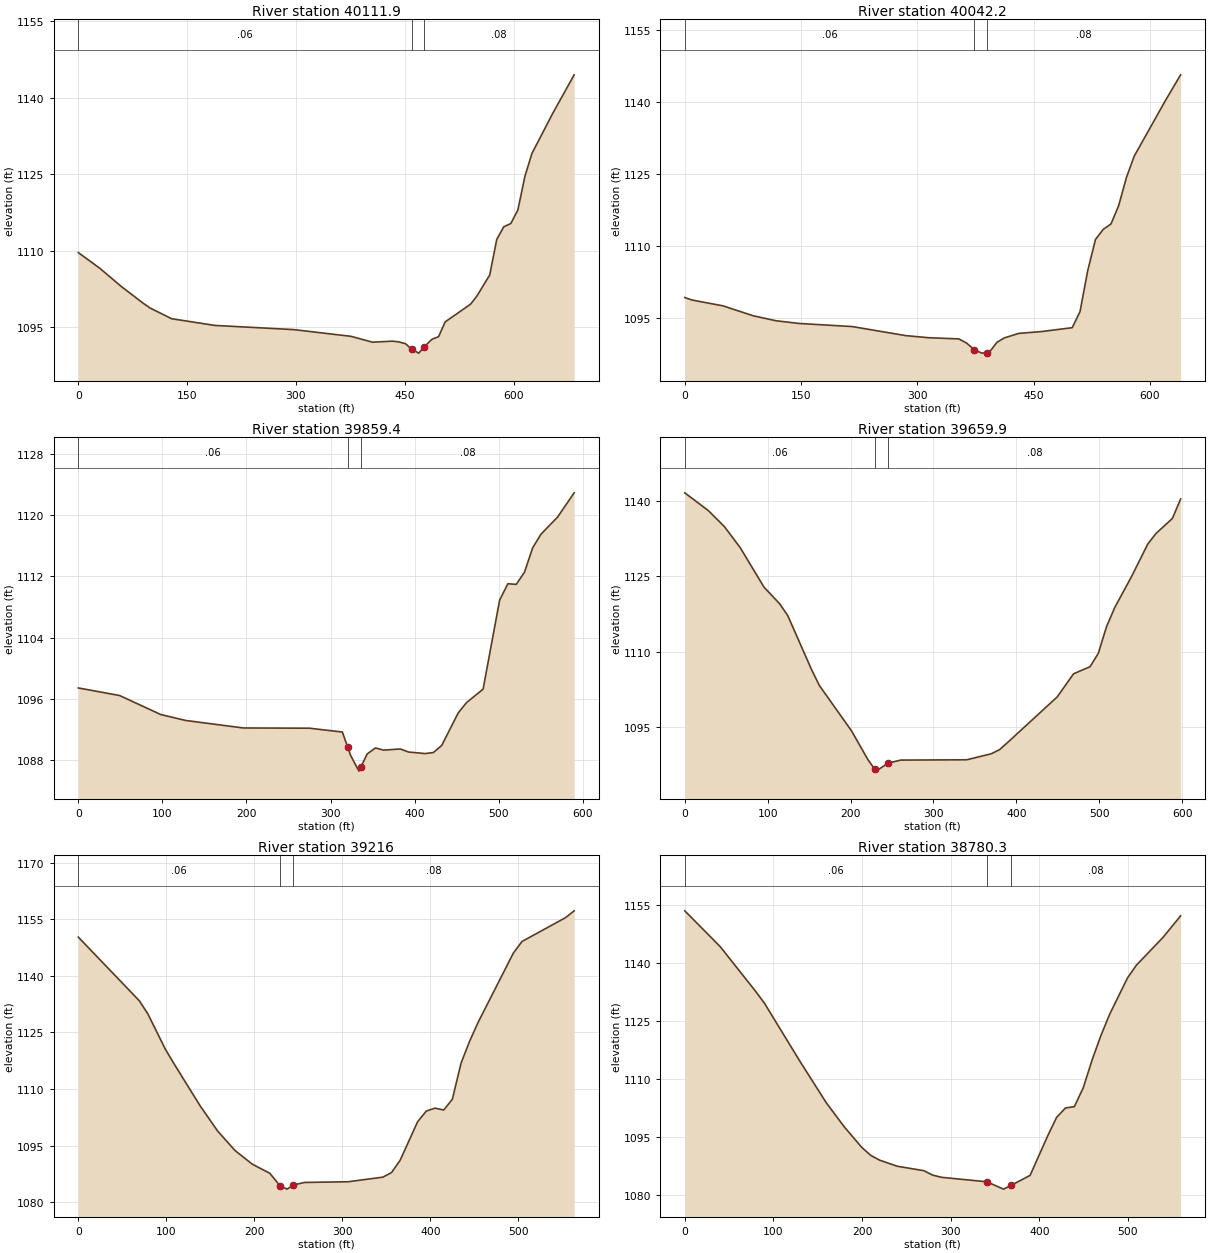
Type RM Length L Ch R = 1 ,40111.9 ,78.6,69.6,63.4
XS GIS Cut Line= 5
     1738795.978       413704.84     1739199.602      413664.839
     1739294.654      413696.089     1739319.151      413752.414
     1739435.279      413761.194
#Sta/Elev= 30
       0 1109.65    29.7 1106.56    59.4 1102.99      89 1099.77    98.9 1098.79
   128.6 1096.69     188 1095.38   296.8 1094.56   375.9 1093.24   405.6 1092.09
   432.9  1092.3     442 1092.15   451.1 1091.79   459.8 1090.68   469.3 1089.95
   476.7 1091.18   487.5 1092.67   496.6 1093.17   505.7 1096.07   540.8 1099.55
   549.5 1101.14   567.1 1105.26   576.8 1112.23   586.5  1114.7   596.2 1115.34
   605.9 1117.99   615.6 1124.57   625.3 1129.07   654.4 1137.03   683.5 1144.47
#Mann= 3 , 0 , 0
       0     .06       0   459.8    .045       0   476.7     .08       0
Bank Sta=459.8,476.7
XS Rating Curve= 0 ,0
Exp/Cntr=0.3,0.1

Type RM Length L Ch R = 1 ,40042.2 ,179.6,182.8,183.3
XS GIS Cut Line= 5
     1738833.717      413762.496     1739235.413      413735.286
     1739267.766      413754.318     1739300.937      413803.824
     1739440.487      413811.975
#Sta/Elev= 30
       0 1099.28     9.8 1098.75    49.1 1097.56    88.4 1095.48   117.8 1094.45
   147.3 1093.89     216 1093.24   284.8 1091.36   314.2 1090.92   353.5 1090.67
   363.3 1089.82   373.2 1088.45     383 1087.71   390.2 1087.83   392.8 1087.88
   402.6 1089.96     412 1090.87   430.8 1091.82     460  1092.2   499.7 1093.01
   509.7 1096.32   519.7 1104.89   529.7 1111.38   539.7 1113.48   549.7 1114.61
   559.6 1118.42   569.6 1124.28   579.6 1128.71   619.6 1140.22   639.5 1145.66
#Mann= 3 , 0 , 0
       0     .06       0   373.2    .045       0   390.2     .08       0
Bank Sta=373.2,390.2
XS Rating Curve= 0 ,0
Exp/Cntr=0.3,0.1

Type RM Length L Ch R = 1 ,39859.4 ,204.9,199.5,194.6
XS GIS Cut Line= 3
      1738834.91      413819.028      1739116.16      413905.833
     1739411.299       413916.25
#Sta/Elev= 30
       0 1097.45    49.1 1096.46    98.1 1093.98   127.6 1093.21   196.2 1092.23
   274.7  1092.2     314  1091.7   320.5 1089.69   323.9 1088.64   333.7  1086.6
   336.1 1087.15   343.6 1088.85   353.4 1089.62   363.2 1089.34   382.9 1089.49
   392.8 1089.09   412.5 1088.89   422.3 1089.03   432.2 1089.95   451.8 1094.19
   461.7 1095.54   481.4 1097.29   501.1 1108.92   510.9 1111.04   520.8 1110.96
   530.6 1112.54   540.4 1115.74   550.3 1117.51     570 1119.74   589.7  1122.9
#Mann= 3 , 0 , 0
       0     .06       0   320.5    .045       0   336.1     .08       0
Bank Sta=320.5,336.1
XS Rating Curve= 0 ,0
Exp/Cntr=0.3,0.1

Type RM Length L Ch R = 1 ,39659.9 ,442.8,443.9,440.4
XS GIS Cut Line= 3
     1738855.744      414109.826     1739046.716      414105.486
     1739448.191      414038.212
#Sta/Elev= 30
       0 1141.68    28.6 1138.11    47.8 1134.94    66.9 1130.74    95.5 1122.89
   114.6 1119.53   124.2  1117.2   152.8 1106.48   162.4 1103.25     201 1094.26
   220.8 1088.52     229  1086.6   230.7  1086.2   245.3  1087.8   260.5  1088.4
     340 1088.46   369.7 1089.66   379.7 1090.48   389.6 1091.94   449.2 1100.99
     469 1105.61   488.9 1107.02   498.8 1109.68   508.7 1114.98   518.7 1118.84
   538.5 1124.86   558.4 1131.45   568.3 1133.56   588.2 1136.58   598.1 1140.45
#Mann= 3 , 0 , 0
       0     .06       0     229    .045       0   245.3     .08       0
Bank Sta=229,245.3
XS Rating Curve= 0 ,0
Exp/Cntr=0.3,0.1

Type RM Length L Ch R = 1 ,39216   ,396.4,435.7,395.8
XS GIS Cut Line= 2
     1738976.441      414531.441     1739512.116      414356.759
#Sta/Elev= 30
       0 1150.27    69.2 1133.43    79.1 1129.89    98.8  1120.6   108.7 1116.72
   138.4 1105.56   158.2 1098.91   177.9 1093.75   197.7 1090.09   217.5 1087.69
   229.2 1084.39   237.2 1083.48   244.3 1084.57     257 1085.25   306.4 1085.43
     346 1086.65   355.9 1087.88   365.7 1091.14   385.5 1101.33   395.4 1104.17
   405.3 1104.94   415.2 1104.44     425 1107.31   434.9 1116.88   444.8 1122.78
   454.7 1127.88   494.2 1145.99   504.1 1149.11   553.6 1155.43   563.4 1157.24
#Mann= 3 , 0 , 0
       0     .06       0   229.2    .045       0   244.3     .08       0
Bank Sta=229.2,244.3
XS Rating Curve= 0 ,0
Exp/Cntr=0.3,0.1

Type RM Length L Ch R = 1 ,38780.3 ,251,242.4,233
XS GIS Cut Line= 2
     1739040.729      414788.594     1739579.642      414638.781
#Sta/Elev= 30
       0 1153.53      40 1144.24    79.9 1132.68    89.9 1129.58   129.8 1114.58
   159.8 1103.74   179.8  1097.6   199.8  1092.2   209.8 1090.17   219.7 1088.94
   239.7 1087.35   269.7  1086.2   279.7 1085.05   289.7 1084.48   340.8 1083.32
   359.6 1081.42   368.2 1082.39   389.6 1084.99   409.5 1095.26   419.5 1100.01
   429.5 1102.45   439.5 1102.79   449.5 1107.66   459.5 1114.86   469.4 1121.18
   479.4 1126.76   499.4 1136.12   509.4 1139.42   539.4 1146.61   559.4 1152.23
#Mann= 3 , 0 , 0
       0     .06       0   340.8    .045       0   368.2     .08       0
Bank Sta=340.8,368.2
XS Rating Curve= 0 ,0
Exp/Cntr=0.3,0.1

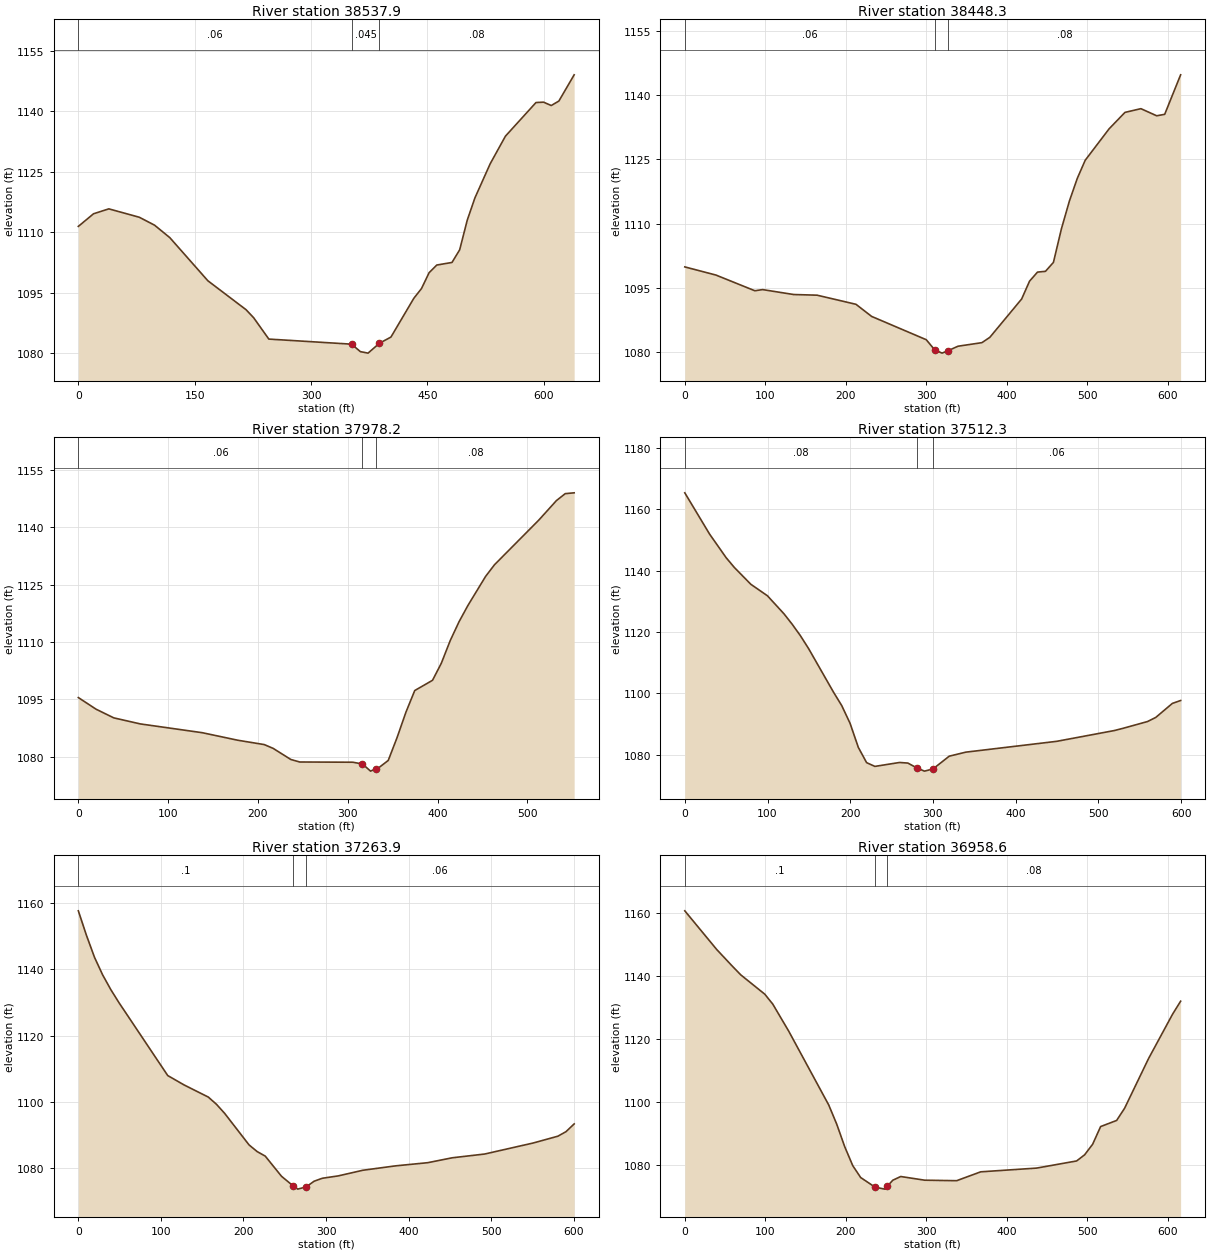
Type RM Length L Ch R = 1 ,38537.9 ,89.3,89.6,90.4
XS GIS Cut Line= 3
     1739153.575      415205.408     1739342.764      414979.364
     1739609.865      414761.916
#Sta/Elev= 30
       0 1111.51    19.6 1114.64    39.3 1115.86    78.6 1113.78    98.3 1111.81
   117.9 1108.73     167 1098.03   216.2 1090.86     226 1088.87   245.6 1083.57
   352.3 1082.31   363.6 1080.46   373.5 1080.09   388.2 1082.54     403 1084.07
   432.5 1093.68   442.4  1096.1   452.2 1100.03   462.1 1101.93   481.7 1102.57
   491.6  1105.7   501.4 1113.07   511.3 1118.59   530.9 1127.02   550.6 1133.88
     590 1142.22   599.8 1142.31   609.7 1141.48   619.5 1142.59   639.2 1149.09
#Mann= 3 , 0 , 0
       0     .06       0   352.3    .045       0   388.2     .08       0
Bank Sta=352.3,388.2
XS Rating Curve= 0 ,0
Exp/Cntr=0.3,0.1

Type RM Length L Ch R = 1 ,38448.3 ,459.2,470.1,479.9
XS GIS Cut Line= 3
     1739212.942      415259.121     1739399.203      415036.576
     1739652.079      414830.709
#Sta/Elev= 30
       0 1099.93    38.7 1098.03    87.1 1094.37    96.7 1094.64   135.4 1093.49
   164.4 1093.34   212.8 1091.21   232.2 1088.39   300.1 1082.96   310.7 1080.58
   319.8 1079.83   327.3  1080.4   339.6 1081.44   369.3 1082.27   379.1  1083.5
   418.7 1092.45   428.5  1096.6   438.4 1098.72   448.3  1098.9   458.2 1100.98
   468.1 1108.79     478 1115.25   487.8 1120.54   497.7 1124.79   527.4 1132.12
   547.1 1135.95   566.9 1136.82   586.6 1135.16   596.5  1135.5   616.3 1144.71
#Mann= 3 , 0 , 0
       0     .06       0   310.7    .045       0   327.3     .08       0
Bank Sta=310.7,327.3
XS Rating Curve= 0 ,0
Exp/Cntr=0.3,0.1

Type RM Length L Ch R = 1 ,37978.2 ,470.2,465.9,459
XS GIS Cut Line= 2
     1739374.557      415405.345     1739906.494      415257.471
#Sta/Elev= 30
       0 1095.44    19.7  1092.4    39.4 1090.13      69 1088.54     138 1086.24
   177.5 1084.27     207 1083.13   216.9 1082.14   236.6 1079.23   246.5 1078.57
   305.6 1078.51   316.4 1078.05   325.4 1076.18     332 1076.86   335.2 1077.19
   345.1 1078.98   354.9 1084.95   364.8 1091.62   374.6 1097.28   394.4 1099.96
   404.2 1104.43   414.1 1110.35   423.9 1115.28   433.8 1119.55   453.5 1127.16
   463.4 1130.21   512.7 1141.89   532.4 1147.02   542.2 1148.83   552.1 1149.04
#Mann= 3 , 0 , 0
       0     .06       0   316.4    .045       0     332     .08       0
Bank Sta=316.4,332
XS Rating Curve= 0 ,0
Exp/Cntr=0.3,0.1

Type RM Length L Ch R = 1 ,37512.3 ,242,248.4,254.4
XS GIS Cut Line= 2
     1739443.945      415842.556     1739999.598      415617.786
#Sta/Elev= 30
       0 1165.32      30 1151.87      50 1144.19    59.9 1141.01    79.9 1135.52
    99.9 1131.79   119.9 1125.92   129.9 1122.49   139.9 1118.73   149.8 1114.53
   179.8 1100.39   189.8 1095.98   199.8 1090.25   209.8  1082.4   219.8 1077.44
   229.8 1076.22   259.7  1077.5   269.7  1077.3   280.4 1075.74   289.7 1074.68
     300 1075.38   319.7 1079.55   339.7 1080.86   449.5 1084.38   519.5 1087.91
   529.5  1088.6   559.4 1090.83   569.4 1092.18   589.4 1096.73   599.4 1097.68
#Mann= 3 , 0 , 0
       0     .08       0   280.4    .045       0     300     .06       0
Bank Sta=280.4,300
XS Rating Curve= 0 ,0
Exp/Cntr=0.3,0.1

Type RM Length L Ch R = 1 ,37263.9 ,299.5,305.3,310.5
XS GIS Cut Line= 2
     1739535.832      416026.745     1740096.633      415811.857
#Sta/Elev= 30
       0 1157.69     9.8 1150.33    19.7  1143.6    29.5 1138.35    39.4  1133.9
    49.2    1130   108.3    1108     128 1105.18   157.5  1101.5   167.4 1099.31
   177.2 1096.61   206.8 1087.08   216.6 1085.07   226.4  1083.7   246.1 1077.62
   260.3 1074.69   265.8 1073.74   276.1 1074.43   285.5 1076.11   295.4 1077.01
     315 1077.74   344.6 1079.43     384 1080.75   423.4 1081.72   452.9 1083.19
   492.3 1084.33   551.3 1087.67   580.9 1089.71   590.7 1091.07   600.6 1093.41
#Mann= 3 , 0 , 0
       0      .1       0   260.3    .045       0   276.1     .06       0
Bank Sta=260.3,276.1
XS Rating Curve= 0 ,0
Exp/Cntr=0.3,0.1

Type RM Length L Ch R = 1 ,36958.6 ,245.7,250.7,255.7
XS GIS Cut Line= 2
     1739647.537      416238.986     1740257.572      416152.833
#Sta/Elev= 30
       0 1160.79    39.8 1148.45    59.6 1143.05    69.6 1140.42    99.4 1134.28
   109.3 1131.14   129.2  1122.5   178.9 1099.03   188.8 1092.95   198.7  1085.8
   208.7 1079.77   218.6 1075.97   236.4 1072.93   248.4  1072.3   251.5 1073.17
   258.4 1075.12   268.3 1076.31   298.1 1075.14   337.8 1074.98   367.7  1077.8
   437.2 1078.99   486.9 1081.26   496.8 1083.21   506.8 1086.58   516.7 1092.19
   536.6 1094.14   546.5 1098.02   576.3 1113.84   606.2 1127.97   616.1 1132.05
#Mann= 3 , 0 , 0
       0      .1       0   236.4    .045       0   251.5     .08       0
Bank Sta=236.4,251.5
XS Rating Curve= 0 ,0
Exp/Cntr=0.3,0.1

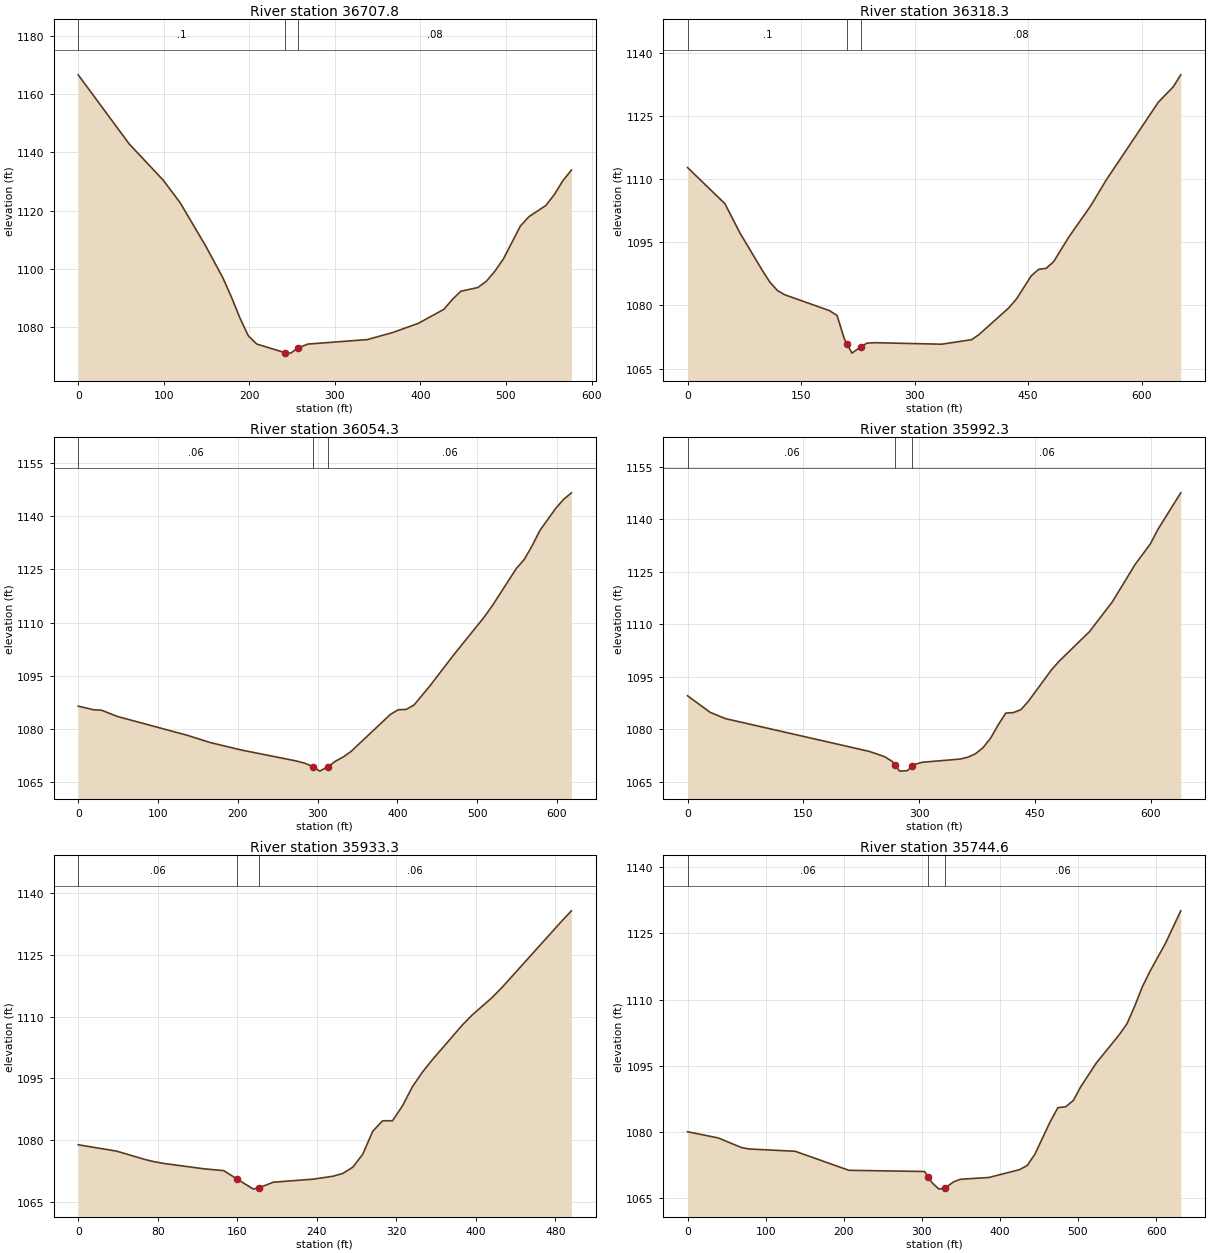
Type RM Length L Ch R = 1 ,36707.8 ,393,389.5,387.9
XS GIS Cut Line= 2
     1739647.145       416435.25     1740221.729      416481.674
#Sta/Elev= 30
       0 1166.55    59.6 1142.87    99.4 1130.44   119.3 1122.65   149.1 1107.85
     169 1097.03   178.9 1090.54   188.8 1083.38   198.8  1077.1   208.7 1074.27
   241.7 1071.32   248.5 1071.16   256.8  1072.9   268.4 1074.26   337.9  1075.8
   367.7 1078.23   397.6 1081.38   427.4 1086.16   437.3 1089.54   447.2 1092.36
   467.1 1093.64   477.1  1095.8     487 1099.23     497 1103.44   516.8  1114.7
   526.8 1117.92   546.6 1121.76   556.6 1125.53   566.5 1130.26   576.5  1133.9
#Mann= 3 , 0 , 0
       0      .1       0   241.7    .045       0   256.8     .08       0
Bank Sta=241.7,256.8
XS Rating Curve= 0 ,0
Exp/Cntr=0.3,0.1

Type RM Length L Ch R = 1 ,36318.3 ,225.6,264.1,268.5
XS GIS Cut Line= 2
     1739610.925      416819.188     1740260.137      416763.335
#Sta/Elev= 30
       0 1112.72    49.4 1104.14    69.1 1097.23    98.7 1088.33   108.6 1085.55
   118.5 1083.56   128.4 1082.52   187.6 1078.74   197.5 1077.61   207.3 1071.95
   210.9 1070.75   217.2 1068.66     229 1070.17     237 1071.03   246.8 1071.14
   335.7 1070.78   375.2 1071.85     385 1073.05   424.5 1079.43   434.4 1081.48
   454.2 1087.04     464 1088.55   473.9  1088.8   483.8 1090.41   503.5 1096.17
   533.1 1103.76   552.9  1109.7     622 1128.24   641.7 1131.89   651.6 1134.73
#Mann= 3 , 0 , 0
       0      .1       0   210.9    .045       0     229     .08       0
Bank Sta=210.9,229
XS Rating Curve= 0 ,0
Exp/Cntr=0.3,0.1

Type RM Length L Ch R = 1 ,36054.3 ,76.5,62,61.1
XS GIS Cut Line= 4
     1739687.817      416925.425     1739936.095      416977.694
     1740012.076      416997.302     1740297.941      416987.093
#Sta/Elev= 30
       0 1086.43    19.5 1085.41    29.3 1085.29    48.8 1083.54   136.6 1078.22
   165.9 1076.14   204.9 1074.04   273.3 1070.97   283.2 1070.39   294.3 1069.39
   302.8  1068.1   313.4 1069.39   322.4 1070.89   332.2 1072.09     342 1073.65
   391.4 1084.12   401.2 1085.42   411.1  1085.5     421 1086.77   440.7 1092.11
   470.3 1100.79   509.7  1111.8   519.6 1114.96   549.2 1125.28   559.1 1127.82
   568.9 1131.65   578.8 1136.04   598.5 1142.22   608.4 1144.78   618.2 1146.62
#Mann= 3 , 0 , 0
       0     .06       0   294.3    .045       0   313.4     .06       0
Bank Sta=294.3,313.4
XS Rating Curve= 0 ,0
Exp/Cntr=0.3,0.1

Type RM Length L Ch R = 1 ,35992.3 ,64.3,59,53.6
XS GIS Cut Line= 3
     1739676.979      416982.008     1740060.813       417063.65
     1740306.439       417045.34
#Sta/Elev= 30
       0  1089.6    29.4 1084.85      49 1083.08   235.4 1073.72   255.1 1072.23
   264.9 1070.89     269 1069.72   274.7 1068.09   284.5 1068.22   291.3 1069.48
   294.3 1070.03   304.1 1070.62   353.2 1071.54     363 1072.07   372.8 1073.04
   382.6 1074.77   392.4 1077.48   402.3  1081.3   412.1 1084.65     422  1084.8
   431.8 1085.65   441.7 1088.12   471.2 1096.98   481.1 1099.45   520.5 1107.91
   550.1 1116.41   579.6 1127.08   599.3 1132.94   609.2 1137.12   638.7 1147.53
#Mann= 3 , 0 , 0
       0     .06       0     269    .045       0   291.3     .06       0
Bank Sta=269,291.3
XS Rating Curve= 0 ,0
Exp/Cntr=0.3,0.1

Type RM Length L Ch R = 1 ,35933.3 ,182.7,188.7,194.6
XS GIS Cut Line= 3
     1739798.067      417041.824     1739873.587       417101.72
      1740273.11      417090.466
#Sta/Elev= 30
       0 1078.96    38.6 1077.42    67.5 1075.37    77.1 1074.82    86.8 1074.41
   126.4 1073.14   146.4  1072.7   159.5  1070.7   176.3 1068.22   181.6 1068.61
   186.3 1068.96   196.3  1069.9   236.3 1070.63   256.3 1071.34   266.2 1072.02
   276.2 1073.53   286.2 1076.66   296.2  1082.2   306.2 1084.76   316.2 1084.78
   326.2  1088.4   336.2 1093.01   346.2 1096.53   356.2 1099.53   386.2 1107.89
   396.2 1110.34   416.1 1114.54   426.1 1116.98   486.1 1133.02   496.1 1135.58
#Mann= 3 , 0 , 0
       0     .06       0   159.5    .045       0   181.6     .06       0
Bank Sta=159.5,181.6
XS Rating Curve= 0 ,0
Exp/Cntr=0.3,0.1

Type RM Length L Ch R = 1 ,35744.6 ,80.1,80.1,80.1
XS GIS Cut Line= 4
     1739775.226      417034.519     1739920.241      417280.308
     1740017.947      417303.673     1740263.383      417291.488
#Sta/Elev= 30
       0 1080.01    39.4  1078.6    68.9 1076.43    78.7  1076.1   137.8 1075.58
   206.6 1071.26   303.6 1070.99   308.1 1069.78   312.8 1068.51   321.9 1066.99
   330.3  1067.3   340.2 1068.59   349.3 1069.22   385.8 1069.63   425.2 1071.41
     435 1072.35   444.8 1074.91   464.5 1082.32   474.3 1085.48   484.1 1085.66
     494  1087.1   503.8  1090.3   523.4  1095.6   552.9 1102.03   562.8 1104.53
   572.6 1108.48   582.4 1112.89   592.3 1116.45   611.9 1122.71   631.6 1130.13
#Mann= 3 , 0 , 0
       0     .06       0   308.1    .045       0   330.3     .06       0
Bank Sta=308.1,330.3
XS Rating Curve= 0 ,0
Exp/Cntr=0.3,0.1