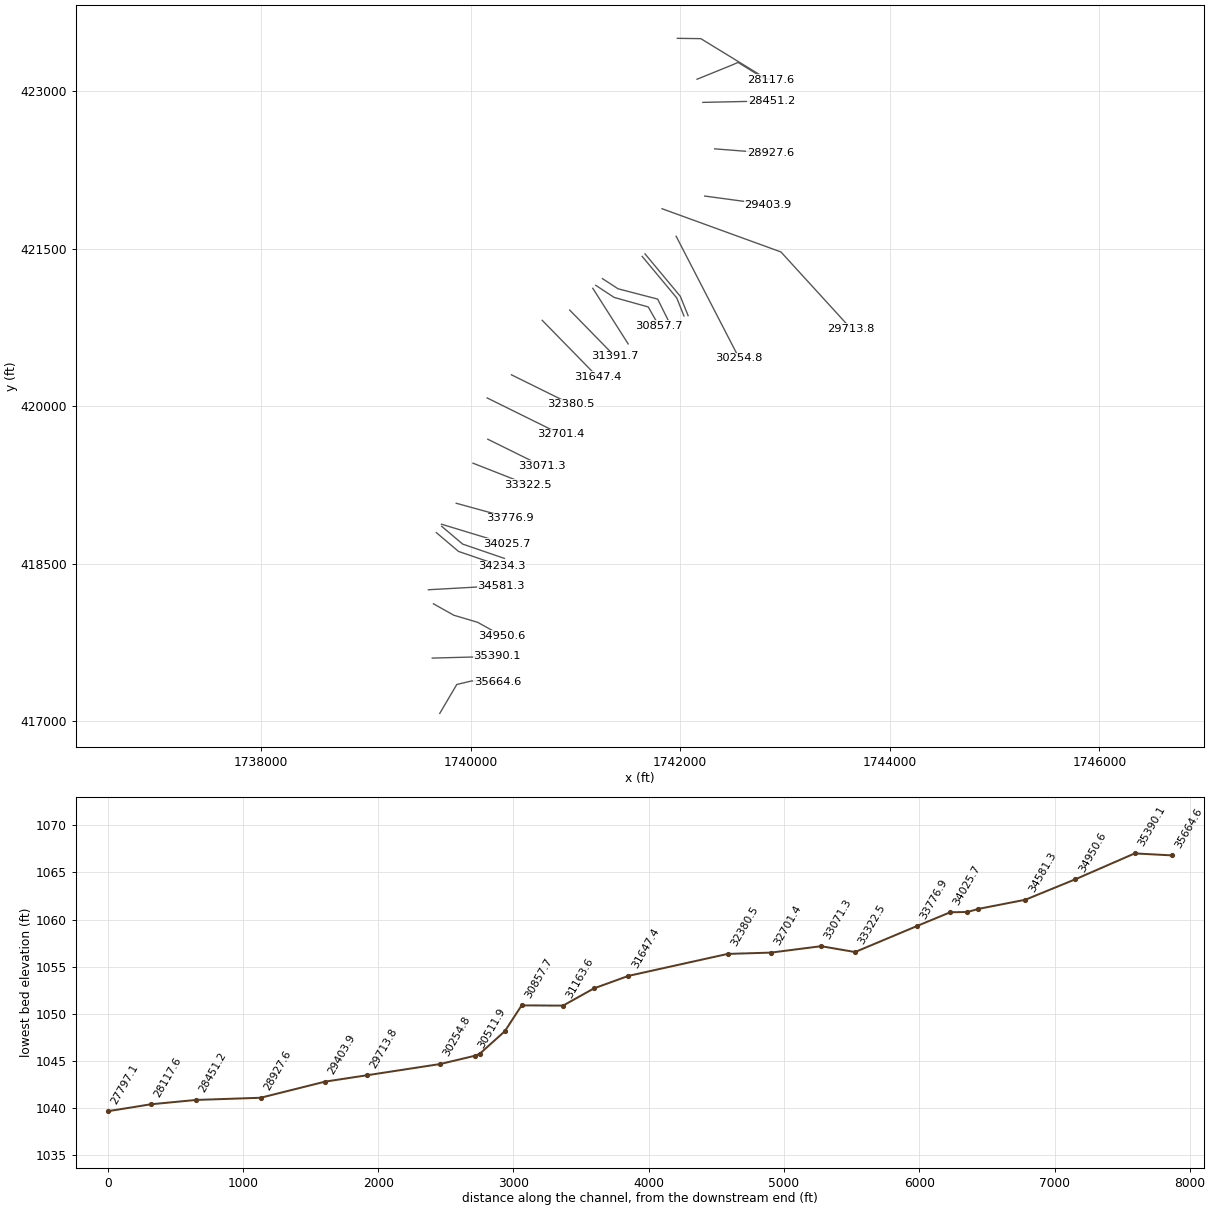
HEC-RAS study RFkMrcleRn.prj: RFkMrcleRn

--- RFkMrcleRn.g01 (geometry) --- (continued)

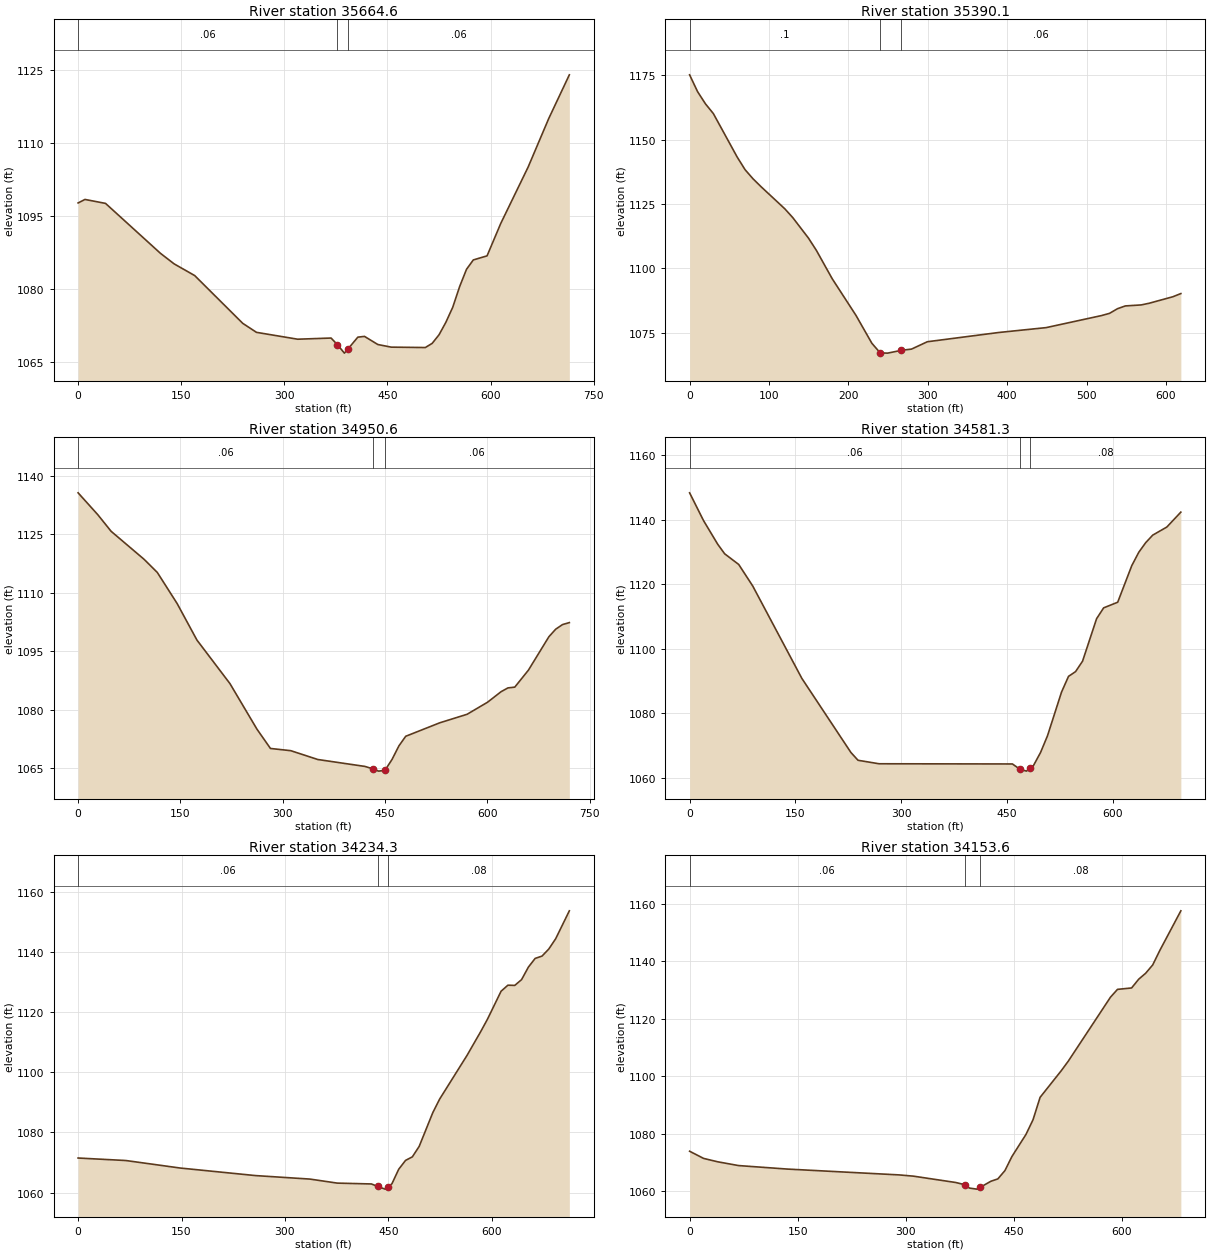
Type RM Length L Ch R = 1 ,35664.6 ,279.7,274.5,269.1
XS GIS Cut Line= 4
     1739706.324      417075.171       1739868.6      417350.215
     1740010.478      417384.142     1740259.498       417371.78
#Sta/Elev= 30
       0 1097.67      10 1098.39    39.9 1097.58   119.8 1087.32   139.7 1085.15
   169.6 1082.75   239.5 1072.93   259.5 1071.08   319.4 1069.67     368 1069.91
   377.2 1068.55   387.4 1066.81   392.2  1067.6   406.9 1070.09   416.6 1070.25
     436 1068.58   455.5 1068.04   505.1 1067.96   515.1 1068.82   525.1 1070.59
     535 1073.15     545 1076.24     555 1080.48     565 1084.03   574.9 1085.96
   594.9  1086.8   614.8 1093.45   654.7 1105.06   684.6 1115.01   714.6    1124
#Mann= 3 , 0 , 0
       0     .06       0   377.2    .045       0   392.2     .06       0
Bank Sta=377.2,392.2
XS Rating Curve= 0 ,0
Exp/Cntr=0.3,0.1

Type RM Length L Ch R = 1 ,35390.1 ,441.4,439.5,430.9
XS GIS Cut Line= 2
     1739634.702       417601.96     1740253.298      417618.062
#Sta/Elev= 30
       0 1175.15      10 1168.63      20 1163.86    29.9  1160.1    59.9 1143.22
    69.9 1138.28    79.8 1134.78    89.8 1131.74   119.8 1123.13   129.8 1119.73
   149.7 1111.72   159.7 1106.94   179.6 1095.94   209.6 1081.67   229.6 1070.84
   240.1 1067.11   249.5 1067.02   266.7 1068.11   279.5 1068.58   299.4 1071.44
   389.2 1075.03   449.1 1076.93     519 1081.62     529 1082.48     539 1084.28
   548.9 1085.36   568.9 1085.75   578.9  1086.4   608.8 1088.93   618.8 1090.16
#Mann= 3 , 0 , 0
       0      .1       0   240.1    .045       0   266.7     .06       0
Bank Sta=240.1,266.7
XS Rating Curve= 0 ,0
Exp/Cntr=0.3,0.1

Type RM Length L Ch R = 1 ,34950.6 ,367.3,369.3,376.6
XS GIS Cut Line= 4
     1739645.646      418119.218     1739839.803      418010.334
     1740067.668      417942.626     1740295.109      417816.876
#Sta/Elev= 30
       0  1135.6      29 1129.97    48.4 1125.74    96.8 1118.55   116.1  1115.2
   145.2 1107.22   174.2 1097.87   222.6 1086.71   262.2 1075.03     282 1070.08
   311.8 1069.51   351.4 1067.25   420.7 1065.47   432.8 1064.81   440.5 1064.27
   449.9 1064.47   460.3 1067.28   470.3 1070.73   480.3  1073.2   530.3 1076.66
   570.3 1078.84   600.3 1081.93   620.2 1084.64   630.2  1085.6   640.2  1085.8
   660.2 1090.15   690.2 1098.71   700.2 1100.65   710.2 1101.83   720.2 1102.34
#Mann= 3 , 0 , 0
       0     .06       0   432.8    .045       0   449.9     .06       0
Bank Sta=432.8,449.9
XS Rating Curve= 0 ,0
Exp/Cntr=0.3,0.1

Type RM Length L Ch R = 1 ,34581.3 ,356.5,347,326.8
XS GIS Cut Line= 2
     1739597.854      418252.932     1740292.956      418291.591
#Sta/Elev= 30
       0 1148.35    19.9 1139.68    39.8 1132.43    49.7 1129.45    69.6 1126.15
    89.5 1119.46   159.1 1090.83   228.7 1067.85   238.7 1065.46   268.5 1064.38
   457.5 1064.32   467.7 1062.75   477.4  1062.1   482.7 1063.02   487.3 1063.82
   497.3 1067.85   507.2 1073.05   527.1  1086.6     537 1091.47     547 1092.94
   556.9 1096.18   576.8 1109.35   586.8  1112.7   606.7 1114.44   626.6 1125.76
   636.5  1129.9   646.4 1132.91   656.4 1135.25   676.3 1137.74   696.2 1142.37
#Mann= 3 , 0 , 0
       0     .06       0   467.7    .045       0   482.7     .08       0
Bank Sta=467.7,482.7
XS Rating Curve= 0 ,0
Exp/Cntr=0.3,0.1

Type RM Length L Ch R = 1 ,34234.3 ,80.4,80.6,80.4
XS GIS Cut Line= 3
     1739673.734      418797.039     1739885.121      418618.007
     1740297.222      418477.081
#Sta/Elev= 30
       0 1071.48    69.2 1070.65   148.4 1068.14   257.2 1065.64   336.4 1064.47
     376 1063.13   425.5 1062.85   434.5 1062.04   445.3 1061.13   449.6  1061.9
   455.2  1062.9   465.1 1067.75     475 1070.69   484.9 1071.88   494.8 1075.37
   514.6 1086.62   524.5 1091.11   564.1 1105.61   583.9  1113.5   593.8 1117.67
   613.6    1127   623.5    1129   633.4 1128.93   643.3 1130.85   653.2 1135.02
     663 1137.91     673 1138.69   682.8 1141.04   692.8 1144.47   712.6 1153.75
#Mann= 3 , 0 , 0
       0     .06       0   434.5    .045       0   449.6     .08       0
Bank Sta=434.5,449.6
XS Rating Curve= 0 ,0
Exp/Cntr=0.3,0.1

Type RM Length L Ch R = 1 ,34153.6 ,127.3,127.9,128.8
XS GIS Cut Line= 3
     1739724.932      418857.075     1739924.793      418687.805
     1740322.602      418551.767
#Sta/Elev= 30
       0 1073.97    19.4 1071.48    38.8 1070.31    67.9 1068.99   135.8 1067.77
   291.2 1065.74   310.8 1065.31   369.5 1063.11   379.2 1062.52   382.2  1062.1
     389 1061.15   398.8  1060.8     404 1061.48   418.4 1063.53   428.1 1064.35
   437.9 1067.22   447.7 1072.14   467.2 1079.82     477 1084.92   486.8  1092.7
   516.1 1101.93   525.9 1105.26   584.6 1127.53   594.3 1130.23   613.9 1130.72
   623.7 1133.75   633.4 1135.83   643.2 1138.72     653 1143.72   682.3 1157.53
#Mann= 3 , 0 , 0
       0     .06       0   382.2    .045       0     404     .08       0
Bank Sta=382.2,404
XS Rating Curve= 0 ,0
Exp/Cntr=0.3,0.1

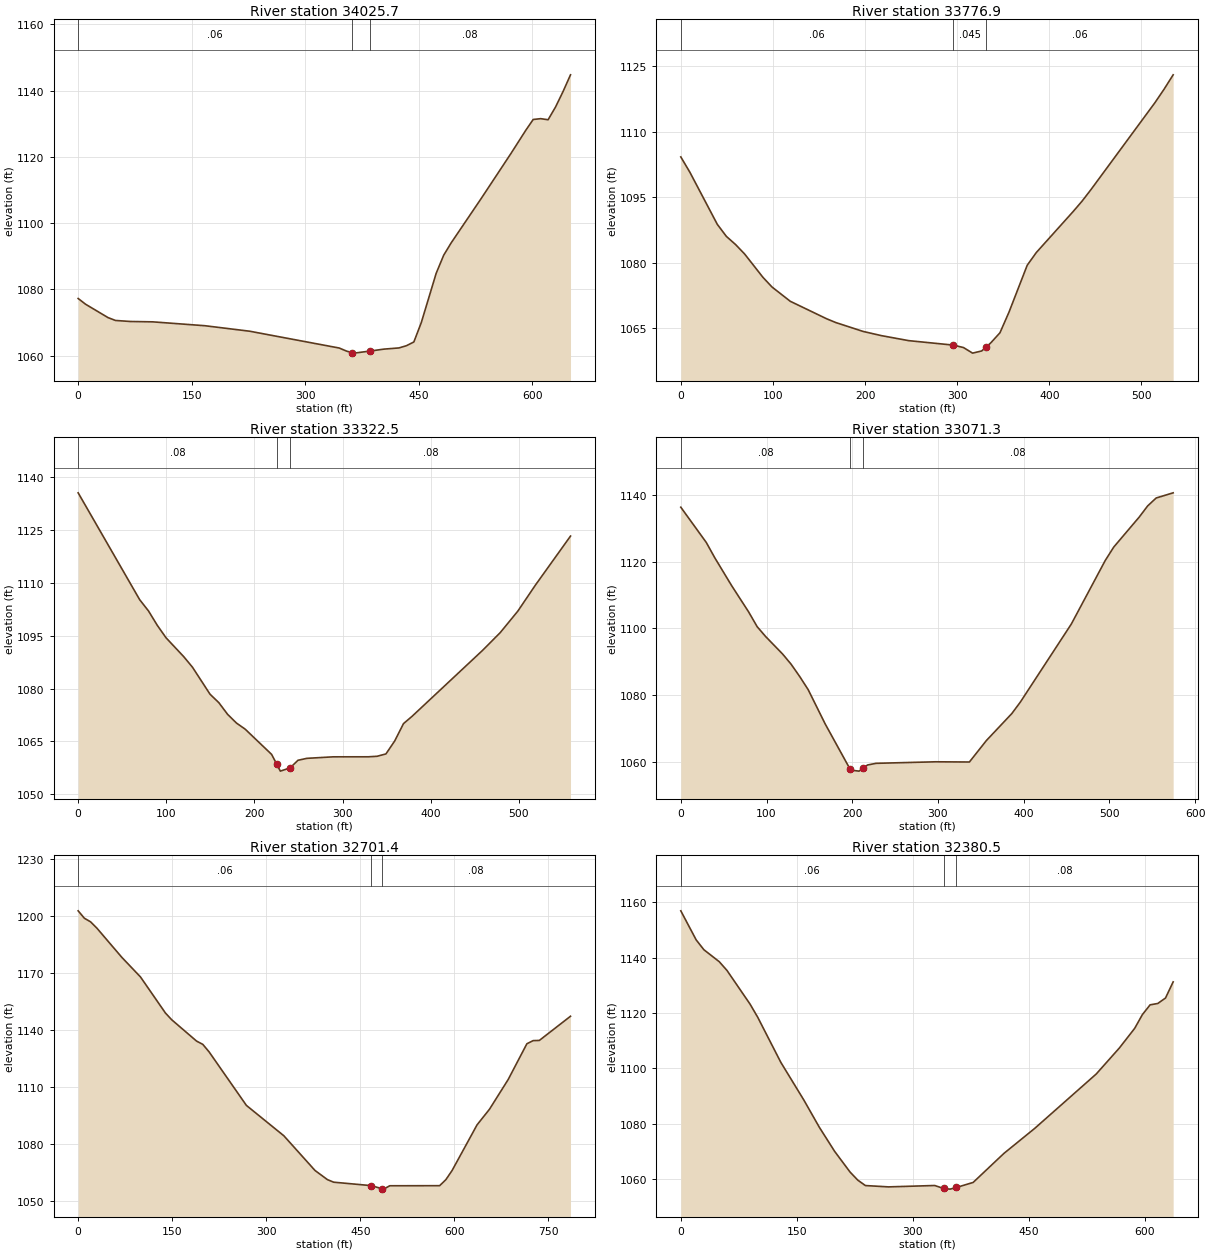
Type RM Length L Ch R = 1 ,34025.7 ,247.9,248.8,249
XS GIS Cut Line= 2
     1739723.017      418877.251     1740345.275      418688.351
#Sta/Elev= 30
       0 1077.26     9.8 1075.53    39.4  1071.5    49.3 1070.63      69 1070.32
    98.5 1070.21   167.5 1069.04   226.6 1067.38   344.8 1062.31   354.7 1061.36
     362 1060.92   364.6 1060.77     385 1061.38     404 1061.98   423.7 1062.34
   433.5    1063   443.4 1064.14   453.2 1069.98   472.9 1084.88   482.8 1090.32
   492.6 1094.02   532.1 1107.36   571.5 1120.98   591.2 1128.02     601 1131.29
   610.9 1131.54   620.7 1131.21   630.6 1135.09   640.4  1139.7   650.3 1144.77
#Mann= 3 , 0 , 0
       0     .06       0     362    .045       0     385     .08       0
Bank Sta=362,385
XS Rating Curve= 0 ,0
Exp/Cntr=0.3,0.1

Type RM Length L Ch R = 1 ,33776.9 ,457.2,454.4,449.6
XS GIS Cut Line= 2
      1739863.44      419076.799     1740378.786        418935.5
#Sta/Elev= 30
       0 1104.25     9.9 1100.72    39.6 1088.81    49.5 1086.03    59.4 1084.18
    69.3    1082    89.1 1076.67      99 1074.44   118.8 1071.17   158.3 1067.16
   168.2  1066.3   197.9 1064.26   217.7  1063.3   247.4 1062.15   295.7 1061.13
   306.8 1060.57   316.7 1059.29   326.6 1059.79   331.2 1060.65   336.4 1061.63
   346.4 1063.95   356.2 1068.67     376 1079.43   385.9 1082.35   425.5 1091.65
   435.4 1094.08   445.3 1096.79   514.6 1116.67   524.5 1119.75   534.4 1123.06
#Mann= 3 , 0 , 0
       0     .06       0   295.7    .045       0   331.2     .06       0
Bank Sta=295.7,331.2
XS Rating Curve= 0 ,0
Exp/Cntr=0.3,0.1

Type RM Length L Ch R = 1 ,33322.5 ,253.1,251.2,249.3
XS GIS Cut Line= 2
     1740023.707      419458.414     1740543.829      419254.565
#Sta/Elev= 30
       0 1135.61    69.8 1105.25    79.8 1102.06    89.8 1097.96    99.8  1094.4
   119.7 1089.09   129.7 1086.07   149.6 1078.41   159.6    1076   169.6 1072.67
   179.6 1070.21   189.5 1068.47   219.5  1061.3   225.3 1058.52   229.4 1056.55
   240.5 1057.48   249.4 1059.63   259.4 1060.18   289.3 1060.61   329.2 1060.62
   339.2 1060.77   349.2 1061.44   359.1  1065.1   369.1 1070.04   379.1 1072.18
   458.9 1090.87   478.8 1095.88   498.8 1101.99   518.7 1109.37   558.6 1123.32
#Mann= 3 , 0 , 0
       0     .08       0   225.3    .045       0   240.5     .08       0
Bank Sta=225.3,240.5
XS Rating Curve= 0 ,0
Exp/Cntr=0.3,0.1

Type RM Length L Ch R = 1 ,33071.3 ,369.3,369.9,370.5
XS GIS Cut Line= 2
     1740164.952      419686.571     1740680.171      419432.631
#Sta/Elev= 30
       0  1136.4    29.7 1125.83    39.6 1121.24    59.4 1112.82    79.2 1104.94
    89.1 1100.53      99 1097.57   118.8 1092.32   128.7 1089.26   138.6 1085.62
   148.6 1081.63   168.4 1071.36   197.2  1057.9   198.1 1057.47     208 1057.17
   212.5 1058.01   217.9 1059.02   227.8 1059.51   297.1 1059.97   336.7 1059.91
   356.5 1066.35   386.2 1074.46   396.1 1077.89   455.6 1101.33   495.2 1120.42
   505.1 1124.44   534.8 1133.44   544.7  1136.8   554.6 1139.17   574.4 1140.72
#Mann= 3 , 0 , 0
       0     .08       0   197.2    .045       0   212.5     .08       0
Bank Sta=197.2,212.5
XS Rating Curve= 0 ,0
Exp/Cntr=0.3,0.1

Type RM Length L Ch R = 1 ,32701.4 ,321.6,320.9,317.4
XS GIS Cut Line= 2
     1740158.336      420080.228     1740862.828         419733.
#Sta/Elev= 30
       0 1202.97     9.9 1199.08    19.9 1197.16    29.8 1193.89    69.6 1178.51
    99.4 1168.18   139.2  1149.2   149.1 1145.67   188.9  1134.4   198.8 1132.69
   208.8 1128.76   268.4 1100.55   328.1 1084.58   377.8 1066.32   397.7 1061.48
   407.6 1060.14   467.7 1058.33   484.5 1056.72   487.2 1056.49   497.1 1058.26
   576.6  1058.3   586.6 1061.48   596.5 1066.29   636.3  1090.3   656.2 1098.56
     686 1114.19   715.8    1133   725.8 1134.65   735.7 1134.76   785.4 1147.49
#Mann= 3 , 0 , 0
       0     .06       0   467.7    .045       0   484.5     .08       0
Bank Sta=467.7,484.5
XS Rating Curve= 0 ,0
Exp/Cntr=0.3,0.1

Type RM Length L Ch R = 1 ,32380.5 ,741.9,733.1,713.4
XS GIS Cut Line= 2
     1740390.333      420300.342     1740961.359      420018.896
#Sta/Elev= 30
       0 1156.97    19.9 1146.45    29.8 1142.92    49.7 1138.58    59.7 1135.42
    89.5 1123.26    99.5 1118.47   129.3  1102.2   159.2 1088.51     179 1078.77
   198.9 1070.01   218.8 1062.54   228.8 1059.61   238.7 1057.64   268.6 1057.16
   328.3 1057.66   339.7  1056.6   348.2 1056.35   356.4 1056.95     378 1058.77
   417.8 1069.27   457.6 1078.31   537.2 1097.99     567 1107.36   586.9  1114.5
   596.8 1119.44   606.8 1122.98   616.7 1123.47   626.7 1125.44   636.6 1131.28
#Mann= 3 , 0 , 0
       0     .06       0   339.7    .045       0   356.4     .08       0
Bank Sta=339.7,356.4
XS Rating Curve= 0 ,0
Exp/Cntr=0.3,0.1

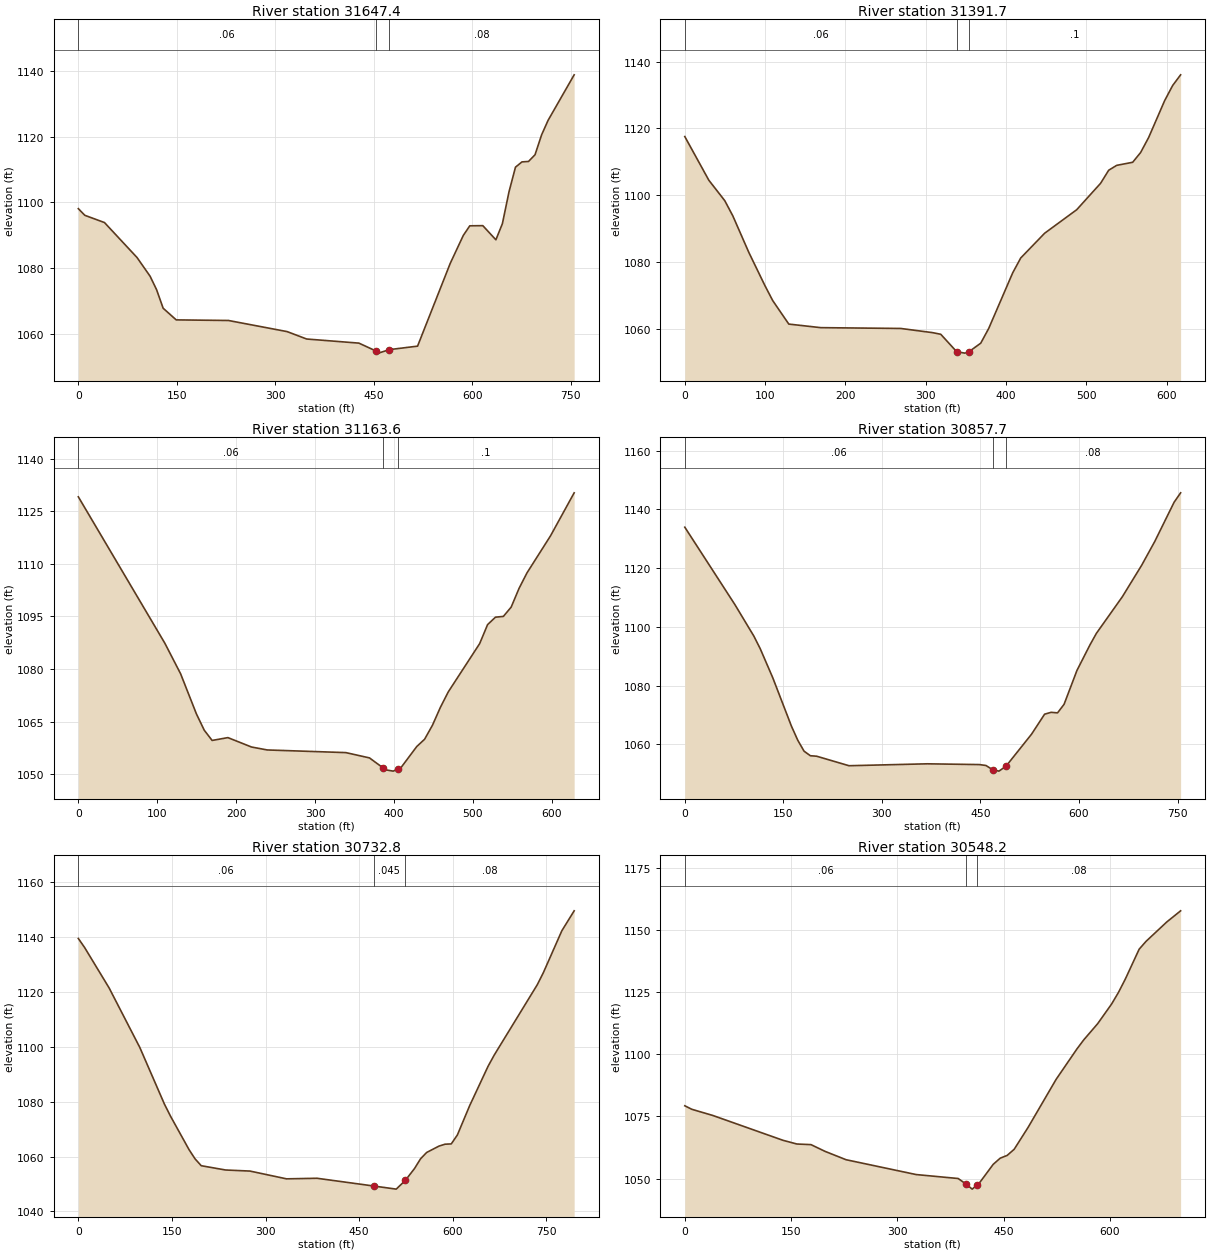
Type RM Length L Ch R = 1 ,31647.4 ,255.6,255.7,255.6
XS GIS Cut Line= 2
     1740684.088      420819.309     1741212.549      420279.762
#Sta/Elev= 30
       0 1098.05     9.9 1096.02    39.8 1093.82    89.4 1083.16   109.3 1077.46
   119.2 1073.35   129.2  1067.7   149.1 1064.15   228.6 1063.97     318 1060.58
   347.8 1058.32   427.3 1057.07   453.3 1054.68   457.1 1054.02   473.9 1055.09
   516.7 1056.15   566.4 1081.35   586.3 1089.87   596.2 1092.82   616.1 1092.87
     636 1088.56   645.9 1093.48   655.9 1103.13   665.8 1110.69   675.7  1112.3
   685.7 1112.44   695.6 1114.48   705.6 1120.54   715.5 1124.97   755.2 1138.84
#Mann= 3 , 0 , 0
       0     .06       0   453.3    .045       0   473.9     .08       0
Bank Sta=453.3,473.9
XS Rating Curve= 0 ,0
Exp/Cntr=0.3,0.1

Type RM Length L Ch R = 1 ,31391.7 ,232.6,228.1,223.3
XS GIS Cut Line= 2
     1740946.081      420917.084     1741378.114      420475.987
#Sta/Elev= 30
       0 1117.57    29.9  1104.5    49.8 1098.35    59.8 1093.81    79.7 1082.88
    99.6    1073   109.5 1068.42   129.5 1061.39   169.3 1060.32   268.9 1060.08
   308.7 1058.82   318.7 1058.34   338.5 1053.13   348.6 1052.69   353.4 1053.04
   368.5 1055.67   378.4 1060.06   408.3 1076.74   418.3 1081.19   448.1 1088.61
     488 1095.65   517.8 1103.58   527.8 1107.47   537.8 1108.94   557.7 1109.86
   567.6 1112.79   577.6 1117.29   597.5 1128.32   607.5 1132.87   617.4 1136.06
#Mann= 3 , 0 , 0
       0     .06       0   338.5    .045       0   353.4      .1       0
Bank Sta=338.5,353.4
XS Rating Curve= 0 ,0
Exp/Cntr=0.3,0.1

Type RM Length L Ch R = 1 ,31163.6 ,286,305.9,326.1
XS GIS Cut Line= 2
     1741166.473      421124.618     1741504.088      420594.851
#Sta/Elev= 30
       0  1129.1   109.7 1087.31   129.6 1078.62   149.6 1067.19   159.5 1062.55
   169.5 1059.61   189.5 1060.42   219.4 1057.74   239.3  1056.9     339 1056.14
   368.9 1054.63   385.8 1051.83   388.9 1051.25   398.9 1050.86   404.6 1051.44
   408.8 1051.86   428.8 1057.88   438.7 1059.95   448.7 1063.96   458.7 1069.04
   468.7 1073.46   508.5 1087.24   518.5 1092.64   528.5 1094.77   538.5 1094.99
   548.4 1097.64   558.4 1102.99   568.4 1107.39   598.3 1117.99   628.2 1130.24
#Mann= 3 , 0 , 0
       0     .06       0   385.8    .045       0   404.6      .1       0
Bank Sta=385.8,404.6
XS Rating Curve= 0 ,0
Exp/Cntr=0.3,0.1

Type RM Length L Ch R = 1 ,30857.7 ,123.6,124.9,128.1
XS GIS Cut Line= 4
      1741194.77      421152.916     1741370.493      421037.552
     1741695.491      420946.941     1741797.893      420767.082
#Sta/Elev= 30
       0 1133.95    76.4 1107.54   105.1 1096.87   114.7 1092.62   133.8 1082.73
   162.4 1066.15     172 1061.38   181.5 1057.69   191.1 1056.13   200.6 1055.97
   249.9 1052.73     369 1053.38   448.4 1053.12   458.3 1052.81   468.8 1051.35
   478.1 1050.89   488.8 1052.55   527.8 1063.49   547.6 1070.28   557.5 1070.91
   567.3 1070.73   577.2 1073.63   596.9 1085.21   616.6 1093.86   626.4  1097.8
   665.9 1110.26   695.4 1121.02   715.2 1129.07   744.7 1142.45   754.6 1145.65
#Mann= 3 , 0 , 0
       0     .06       0   468.8    .045       0   488.8     .08       0
Bank Sta=468.8,488.8
XS Rating Curve= 0 ,0
Exp/Cntr=0.3,0.1

Type RM Length L Ch R = 1 ,30732.8 ,203,184.6,164.2
XS GIS Cut Line= 4
     1741258.691      421216.836     1741407.385      421120.017
     1741785.512      421021.826     1741886.242      420818.872
#Sta/Elev= 30
       0 1139.34     9.9 1136.11    49.3 1121.36    98.6 1099.66     138 1079.07
   147.9 1074.62   177.4 1062.53   187.2 1059.12     197 1056.66     236  1055.1
   275.1 1054.71   333.7 1051.88   382.5 1052.09   473.2 1049.28   509.5 1048.14
     524 1051.29   538.8 1055.62   548.6  1059.2   558.3 1061.48     578 1063.79
   587.8 1064.49   597.7 1064.59   607.5 1067.83   627.2  1078.5   656.8 1092.87
   666.6 1096.92   735.6 1122.51   745.4 1126.93     775 1142.16   794.7  1149.4
#Mann= 3 , 0 , 0
       0     .06       0   473.2    .045       0     524     .08       0
Bank Sta=473.2,524
XS Rating Curve= 0 ,0
Exp/Cntr=0.3,0.1

Type RM Length L Ch R = 1 ,30548.2 ,36.3,36.3,36.3
XS GIS Cut Line= 3
     1741637.864      421428.317     1741967.094      421033.241
     1742036.333      420861.337
#Sta/Elev= 30
       0 1079.28     9.9 1077.87    39.6 1075.38   138.5  1065.4   158.2  1063.9
     178 1063.66   197.8 1060.96   227.5 1057.59   326.4 1051.62   385.7 1050.03
   397.3 1047.71   405.5 1045.76   412.4 1047.41   415.4 1048.13   435.2 1055.74
     445  1058.2   454.9 1059.33   464.8  1061.8   484.6 1070.69     524 1089.94
   553.3 1102.14     563 1105.82   582.6 1112.32   602.1 1120.16   611.8 1124.82
   621.6 1130.26   641.1 1142.26   650.8 1145.41   680.1 1153.22   699.6 1157.69
#Mann= 3 , 0 , 0
       0     .06       0   397.3    .045       0   412.4     .08       0
Bank Sta=397.3,412.4
XS Rating Curve= 0 ,0
Exp/Cntr=0.3,0.1

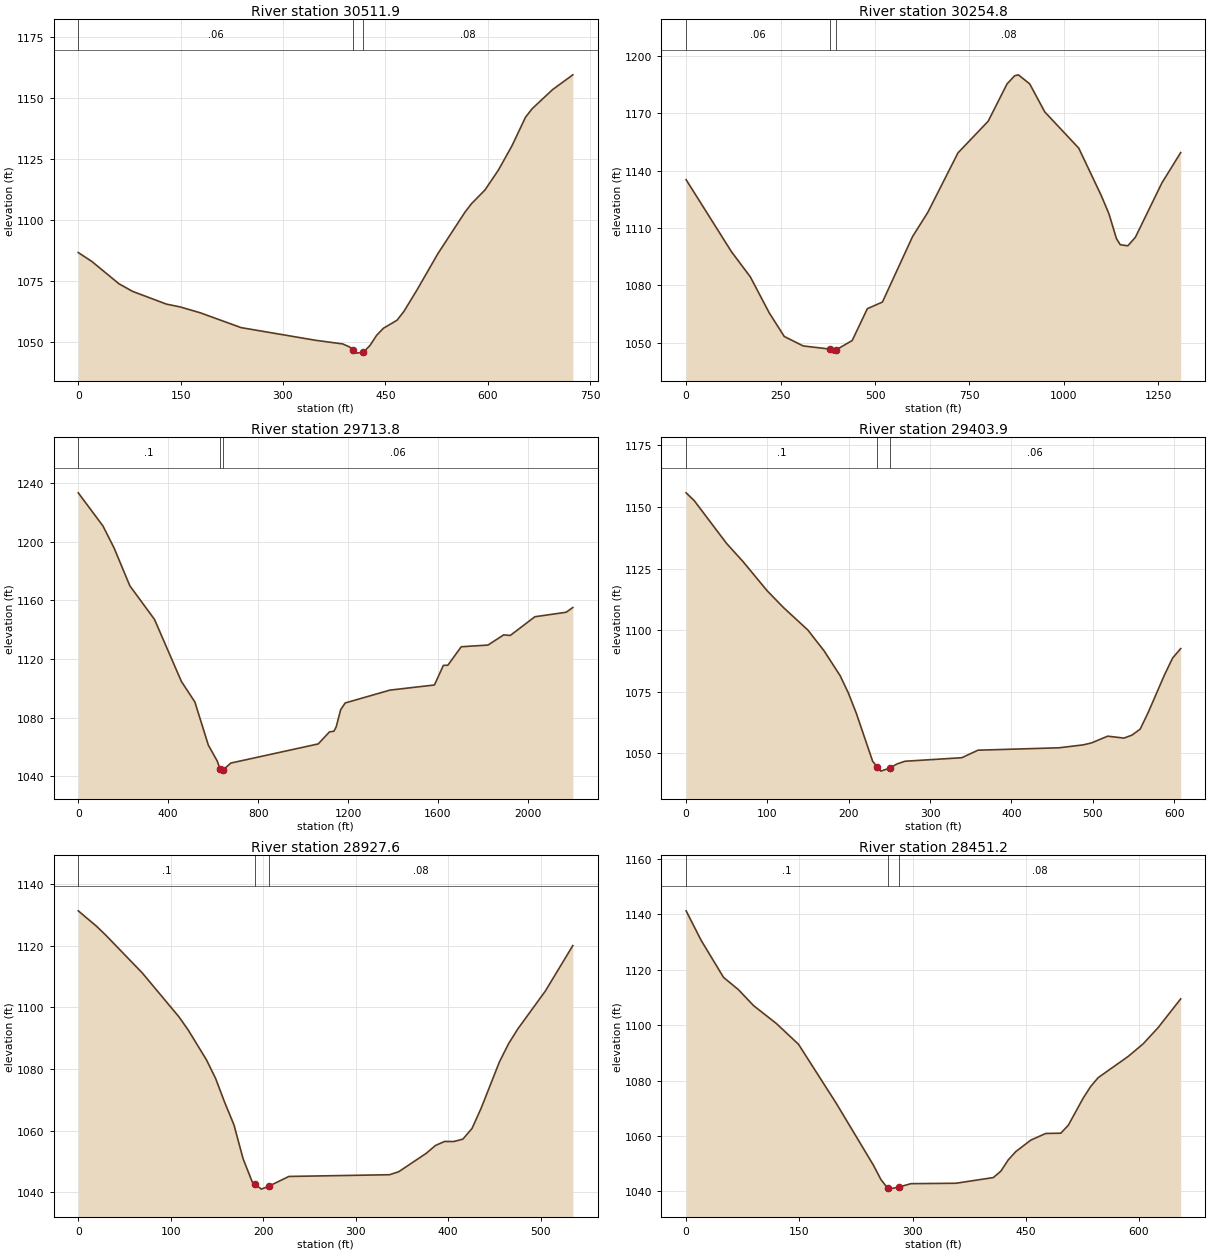
Type RM Length L Ch R = 1 ,30511.9 ,262.3,257.1,252.3
XS GIS Cut Line= 3
     1741664.572       421452.68     1742001.853      421047.943
      1742075.79      420864.375
#Sta/Elev= 30
       0 1086.78    19.9 1083.13    59.6 1073.99    79.5 1070.87   129.2 1065.64
   149.1  1064.5   178.9 1062.07   238.6    1056   347.9  1050.8   387.7  1049.3
   397.6 1048.07   402.8 1046.75   407.6 1045.54   417.9 1045.91   427.4 1048.64
   437.4 1052.89   447.3 1055.75   467.2 1059.04   477.2 1062.62     497 1071.72
   526.8 1086.22   566.4  1103.2   576.3 1106.82   596.1 1112.45   615.9 1120.67
   635.7  1130.6   655.5 1142.29   665.4 1145.82   695.1 1153.58   724.8 1159.65
#Mann= 3 , 0 , 0
       0     .06       0   402.8    .045       0   417.9     .08       0
Bank Sta=402.8,417.9
XS Rating Curve= 0 ,0
Exp/Cntr=0.3,0.1

Type RM Length L Ch R = 1 ,30254.8 ,523.8,541,557.9
XS GIS Cut Line= 2
     1741961.954      421620.303     1742563.389      420457.392
#Sta/Elev= 30
       0 1135.21   119.9 1097.65   169.9  1084.5   219.9 1065.73   259.8 1053.36
   309.8 1048.42   381.3 1046.75   389.8 1044.66   396.9 1046.33   439.7 1051.27
   479.7 1067.86   519.7 1071.34   599.6  1105.6   639.6  1118.1   719.6 1149.22
   799.5 1165.73   849.5 1185.23   869.5 1189.46   879.5 1189.98   909.5 1185.26
   949.4 1170.62  1039.4 1151.69  1099.4 1126.74  1119.3  1117.4  1139.3 1104.41
  1149.3 1101.27  1169.3  1100.7  1189.3 1105.16  1259.3 1133.48  1309.2 1149.38
#Mann= 3 , 0 , 0
       0     .06       0   381.3    .045       0   396.9     .08       0
Bank Sta=381.3,396.9
XS Rating Curve= 0 ,0
Exp/Cntr=0.3,0.1

Type RM Length L Ch R = 1 ,29713.8 ,304.8,309.9,314.6
XS GIS Cut Line= 3
     1741826.755      421882.772     1742961.789      421470.864
     1743631.837      420737.973
#Sta/Elev= 30
       0  1233.5   109.8 1210.89   159.7 1195.74   229.5 1170.02   339.3 1147.04
     459 1104.68   518.9 1090.66   578.8 1061.21   618.7 1050.28     630 1045.15
   638.7 1043.47   645.2 1044.34   678.6 1048.97  1067.8 1062.05  1117.6 1070.25
  1137.6 1070.74  1147.6  1073.7  1167.6 1085.45  1187.5 1090.01  1386.2 1098.77
  1584.8  1102.3  1624.5 1115.68  1644.4 1115.78    1704  1128.4  1823.1 1129.55
  1892.6 1136.49  1922.4 1136.12  2031.7 1148.89  2170.7 1151.95  2200.5 1155.19
#Mann= 3 , 0 , 0
       0      .1       0     630    .045       0   645.2     .06       0
Bank Sta=630,645.2
XS Rating Curve= 0 ,0
Exp/Cntr=0.3,0.1

Type RM Length L Ch R = 1 ,29403.9 ,474.9,476.3,477.5
XS GIS Cut Line= 2
     1742234.656      422003.389      1742837.24      421922.085
#Sta/Elev= 30
       0 1155.75      10 1152.57    49.8 1135.18    69.8  1127.9    99.7 1115.97
   119.6 1109.21   149.5 1100.12   169.5 1091.66   189.4  1081.5   199.4 1074.54
   209.3 1066.21   229.3  1046.8   235.2 1044.41   239.2 1042.79   250.3 1044.01
   259.2  1045.7   269.1  1046.8   338.9 1048.23   358.8 1051.29   458.5 1052.26
   488.4 1053.46   498.4 1054.25   518.3 1056.98   538.3  1056.2   548.2 1057.42
   558.2 1059.84   568.2 1066.71   588.1 1081.86   598.1 1088.71     608 1092.52
#Mann= 3 , 0 , 0
       0      .1       0   235.2    .045       0   250.3     .06       0
Bank Sta=235.2,250.3
XS Rating Curve= 0 ,0
Exp/Cntr=0.3,0.1

Type RM Length L Ch R = 1 ,28927.6 ,474.1,476.4,478.7
XS GIS Cut Line= 2
     1742329.425      422453.067     1742862.557      422411.532
#Sta/Elev= 30
       0 1131.29    19.8 1126.28    29.7 1123.42    69.3 1111.13   108.9 1096.92
   118.8  1092.7   138.6 1083.01   148.5 1076.97   158.4 1069.15   168.4 1061.89
   178.2 1050.96   188.2 1043.37   190.8 1042.76     198 1041.08   205.9 1042.01
   227.8 1045.19   336.7 1045.75   346.6 1046.73   376.3 1052.69   386.2 1055.22
   396.1 1056.53     406 1056.51   415.9 1057.28   425.8 1060.75   435.7 1067.34
   455.5 1082.37   465.4 1088.26   475.3    1093     505 1105.25   534.8 1120.02
#Mann= 3 , 0 , 0
       0      .1       0   190.8    .045       0   205.9     .08       0
Bank Sta=190.8,205.9
XS Rating Curve= 0 ,0
Exp/Cntr=0.3,0.1

Type RM Length L Ch R = 1 ,28451.2 ,325.3,333.6,341.7
XS GIS Cut Line= 2
     1742217.001      422895.734       1742872.2      422909.962
#Sta/Elev= 30
       0 1141.27    19.9 1130.62    49.6 1117.25    69.5 1112.78    89.4 1107.06
   119.2  1100.7   148.9 1093.13   198.6 1071.97   248.2 1049.49   258.2 1044.28
   267.3 1041.13   268.1 1040.85   282.3 1041.61   297.9 1042.82   357.5 1042.97
   407.1 1045.02     417 1047.31     427 1051.44   436.9  1054.4   456.8 1058.54
   476.6 1060.94   496.5 1061.03   506.4 1063.87   526.3 1073.74   536.2 1077.91
   546.1 1081.08   585.8 1088.73   605.7 1093.28   625.6 1099.16   655.4  1109.5
#Mann= 3 , 0 , 0
       0      .1       0   267.3    .045       0   282.3     .08       0
Bank Sta=267.3,282.3
XS Rating Curve= 0 ,0
Exp/Cntr=0.3,0.1

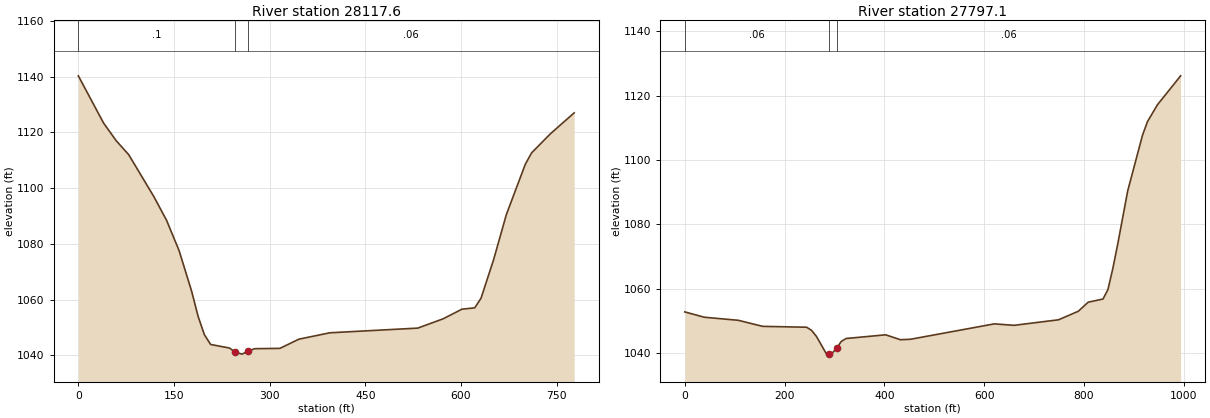
Type RM Length L Ch R = 1 ,28117.6 ,342,320.4,299.2
XS GIS Cut Line= 5
     1742161.037      423116.094     1742499.727      423253.433
     1742552.321      423276.523      1742814.01      423114.892
     1742860.714      423111.983
#Sta/Elev= 30
       0  1140.3    39.5 1123.38    59.3 1117.03      79 1111.99   118.5  1096.9
   138.3 1088.45     158 1077.54   177.8 1062.83   187.7    1054   197.6 1047.38
   207.4 1043.86   237.1 1042.57   245.3 1041.16   256.8 1040.39   265.7 1041.47
   276.6 1042.34   316.1 1042.46   345.7 1045.75   394.2 1048.05   532.1 1049.73
   571.7 1053.05   601.5 1056.53   621.4    1057   631.3 1060.46   651.1 1074.35
     671 1090.49   700.7 1108.54   710.6 1112.65   739.8 1119.44   777.3 1127.01
#Mann= 3 , 0 , 0
       0      .1       0   245.3    .045       0   265.7     .06       0
Bank Sta=245.3,265.7
XS Rating Curve= 0 ,0
Exp/Cntr=0.3,0.1

Type RM Length L Ch R = 1 ,27797.1 ,106.3,107.5,104
XS GIS Cut Line= 4
     1741972.962       423505.87     1742197.307      423502.879
     1742822.552      423120.785     1742859.366      423120.785
#Sta/Elev= 30
       0 1052.77      39 1051.12   107.3 1050.16   156.1 1048.28   244.2 1048.01
   254.1 1047.04     264 1045.13   283.8 1039.74   288.6  1039.7   293.7 1039.65
   305.2 1041.63   313.5 1043.58   323.4 1044.51   402.6 1045.65   432.3 1044.13
   452.1 1044.26   620.4 1049.05   660.1  1048.6   749.2 1050.32   788.8 1052.97
   808.6 1055.79   838.3 1056.77   848.2 1059.71   858.1 1066.32     868 1073.98
   887.8 1090.36   917.5 1107.68   927.4 1111.87   947.2 1117.09   993.9 1126.13
#Mann= 3 , 0 , 0
       0     .06       0   288.6    .045       0   305.2     .06       0
Bank Sta=288.6,305.2
XS Rating Curve= 0 ,0
Exp/Cntr=0.3,0.1