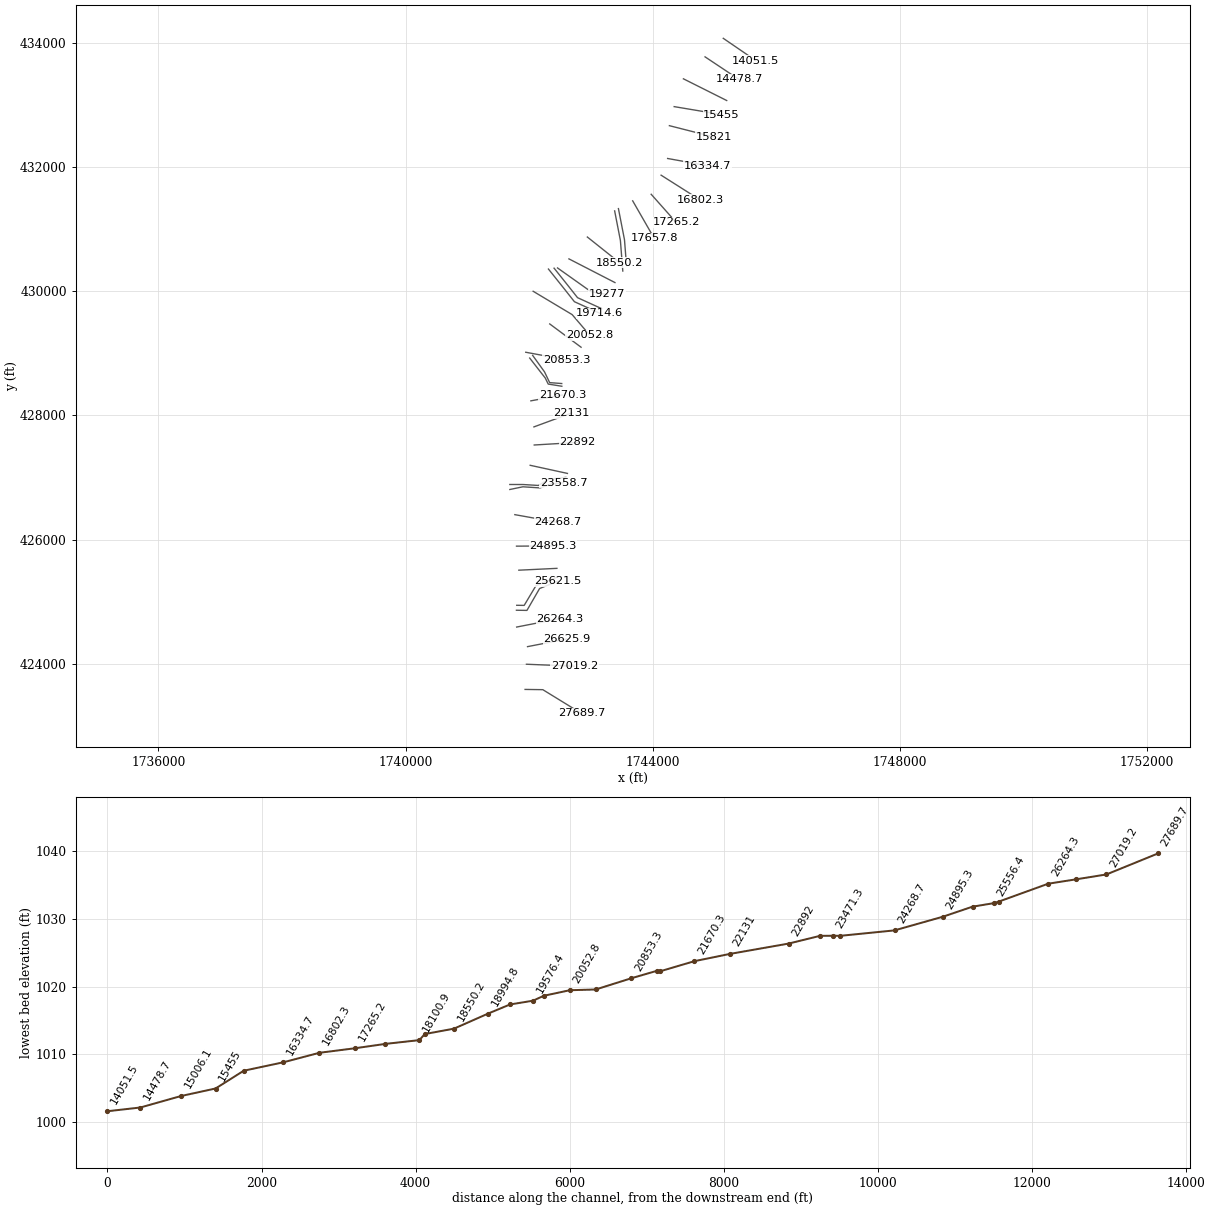
HEC-RAS study RFkMrcleRn.prj: RFkMrcleRn

--- RFkMrcleRn.g01 (geometry) --- (continued)

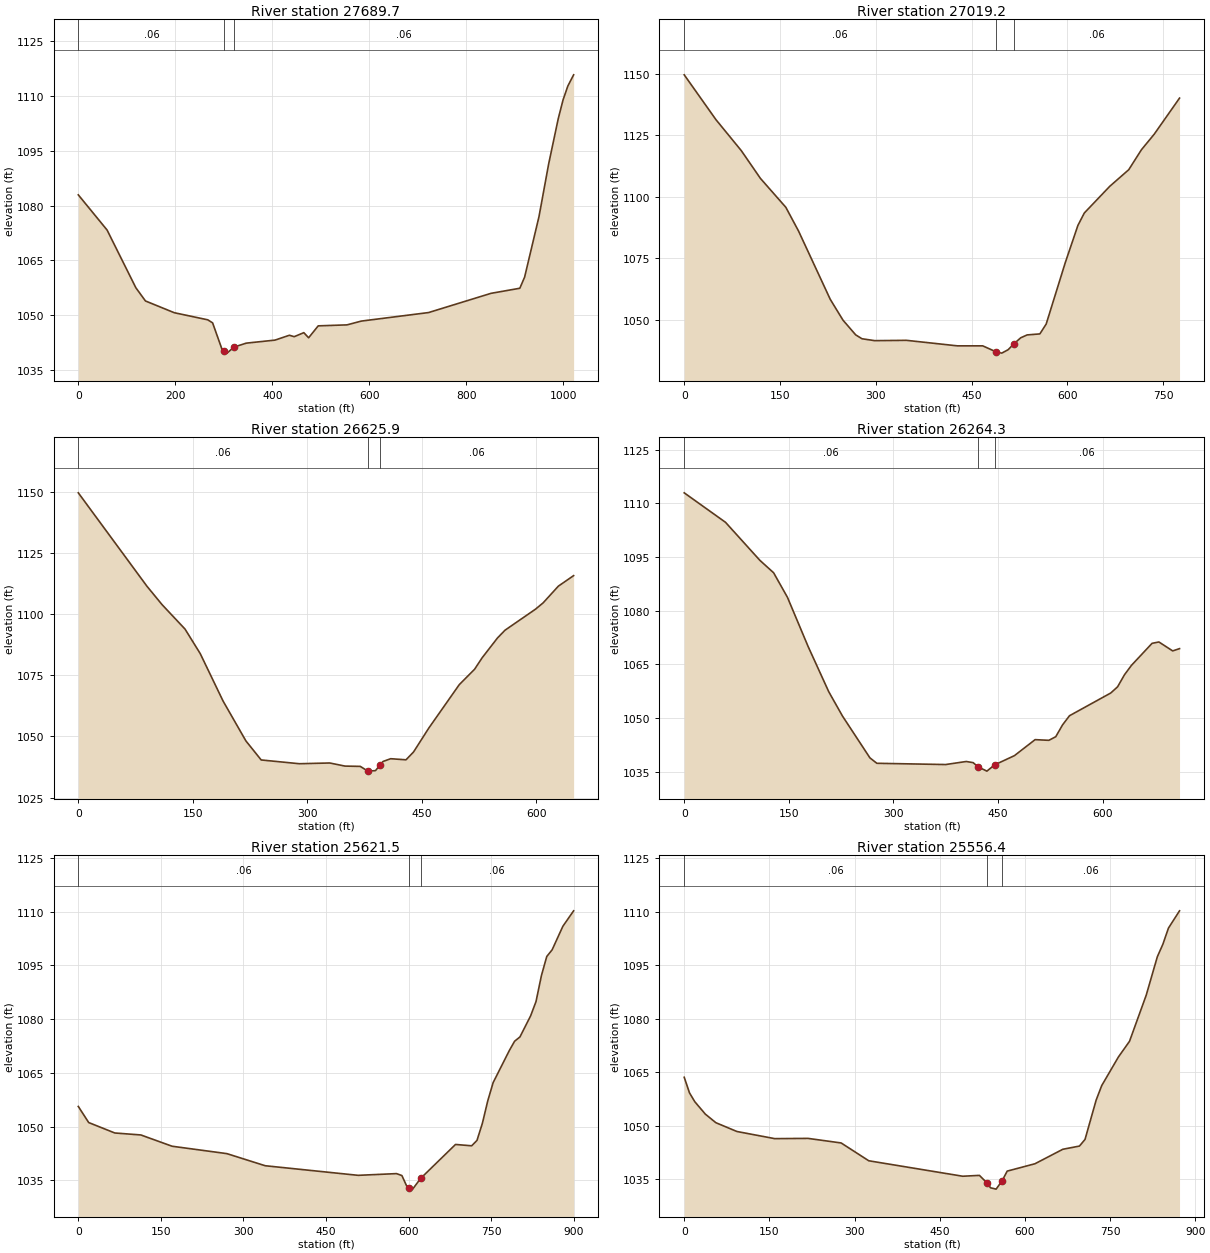
Type RM Length L Ch R = 1 ,27689.7 ,657.7,670.5,683.6
XS GIS Cut Line= 4
     1741933.633      423586.402     1742220.307       423582.58
     1742845.061      423200.785     1742847.108      423200.785
#Sta/Elev= 30
       0 1082.92    59.3  1073.3   118.6 1057.51   138.4 1053.89   197.7 1050.68
   266.9 1048.73   276.8  1047.9   296.6 1040.51     301 1040.11   306.5 1039.62
   320.9 1041.27   346.1 1042.35   405.4 1043.18   435.1 1044.51     445 1044.12
   464.8 1045.22   474.7 1043.82   494.5 1047.08   553.8 1047.35   583.5 1048.39
     722 1050.72   850.7 1055.98     910 1057.37   919.9 1060.42   949.6 1077.02
   969.4 1091.35   989.2 1103.76   999.1 1108.89    1009  1112.7  1020.9 1115.76
#Mann= 3 , 0 , 0
       0     .06       0     301    .045       0   320.9     .06       0
#XS Ineff= 2 , 0
                          464.64         1045.21
Permanent Ineff=
       F       F
Bank Sta=301,320.9
XS Rating Curve= 0 ,0
Exp/Cntr=0.3,0.1

Type RM Length L Ch R = 1 ,27019.2 ,388.3,393.3,399.3
XS GIS Cut Line= 2
     1741955.686      423992.169     1742730.678      423960.356
#Sta/Elev= 30
       0 1149.62    49.7  1131.4    89.5 1118.77   119.3 1107.54   159.1 1095.79
     179 1086.15   228.7 1058.37   248.6 1049.93   268.5 1043.94   278.4 1042.36
   298.3 1041.59     348 1041.72   427.6 1039.48   467.4 1039.48   487.5 1037.14
   497.2 1036.52   507.2  1037.9   516.2 1040.31     527 1042.76     537 1043.92
   556.9 1044.33   566.8 1048.34   596.6 1073.23   616.5 1088.44   626.5 1093.47
   666.3  1104.3   696.1 1111.07     716  1119.2   735.9 1125.48   775.6 1140.16
#Mann= 3 , 0 , 0
       0     .06       0   487.5    .045       0   516.2     .06       0
Bank Sta=487.5,516.2
XS Rating Curve= 0 ,0
Exp/Cntr=0.3,0.1

Type RM Length L Ch R = 1 ,26625.9 ,362,361.5,360.4
XS GIS Cut Line= 2
     1741973.391      424275.452     1742610.402      424399.032
#Sta/Elev= 30
       0 1149.68    89.8 1111.51   109.8  1103.9   139.8 1093.93   159.7 1083.91
   189.7 1064.45   219.6 1048.15   239.6 1040.37   289.5 1038.83   329.4 1039.13
   349.4 1037.86   369.4 1037.74   379.4  1035.8   379.5  1035.8   389.3    1036
   395.4  1038.3   399.3 1039.77   409.3 1040.88   429.3 1040.43   439.2 1043.64
   459.2 1053.43   499.1 1071.19   519.1 1077.47   529.1  1082.2   549.1 1090.27
     559 1093.46     599 1102.08     609 1104.67   628.9 1111.49   648.9  1115.8
#Mann= 3 , 0 , 0
       0     .06       0   379.5    .045       0   395.4     .06       0
Bank Sta=379.5,395.4
XS Rating Curve= 0 ,0
Exp/Cntr=0.3,0.1

Type RM Length L Ch R = 1 ,26264.3 ,636.6,642.8,648.3
XS GIS Cut Line= 2
     1741797.487      424591.022     1742494.705      424726.283
#Sta/Elev= 30
       0 1112.95    59.2 1104.71   108.5 1094.08   128.2  1090.6     148 1083.75
   177.6 1070.02   207.2 1057.37   226.9 1050.56   266.3 1038.86   276.2 1037.35
   374.8    1037   404.4 1037.85   414.3 1037.53   421.3 1036.36     434 1035.16
   445.1 1036.91   473.5 1039.49   503.1 1043.96   522.8 1043.77   532.7 1044.78
   542.5 1048.09   552.4 1050.64   611.6    1057   621.4 1058.73   631.3 1062.11
   641.2 1064.71   670.8 1070.88   680.6 1071.26   700.4 1068.76   710.2  1069.4
#Mann= 3 , 0 , 0
       0     .06       0   421.3    .045       0   445.1     .06       0
Bank Sta=421.3,445.1
XS Rating Curve= 0 ,0
Exp/Cntr=0.3,0.1

Type RM Length L Ch R = 1 ,25621.5 ,65.1,65.1,65.1
XS GIS Cut Line= 4
     1741793.502      424861.536     1741963.878      424858.853
      1742168.45      425211.303     1742466.962      425331.088
#Sta/Elev= 30
       0  1055.6    18.9  1051.1    66.3 1048.19   113.6 1047.64   170.4 1044.49
   269.8 1042.43   339.4 1039.05   508.3 1036.37   577.9 1036.85   587.7 1036.31
   597.4 1033.05   600.4 1032.89   607.2 1032.52   621.9 1035.54   685.1 1044.99
   714.4 1044.61   724.1 1046.13   733.9  1050.9   743.6 1057.13   753.4 1062.25
   782.6 1071.14   792.4  1073.8   802.1    1075   821.6 1080.92   831.3 1084.88
   841.1 1092.12   850.8 1097.45   860.6 1099.33   880.1  1105.9   899.6  1110.2
#Mann= 3 , 0 , 0
       0     .06       0   600.4    .045       0   621.9     .06       0
Bank Sta=600.4,621.9
XS Rating Curve= 0 ,0
Exp/Cntr=0.3,0.1

Type RM Length L Ch R = 1 ,25556.4 ,283.5,276,268.3
XS GIS Cut Line= 4
     1741798.436      424941.468     1741919.013      424939.569
     1742109.379      425256.845     1742463.842      425399.082
#Sta/Elev= 30
       0 1063.62     9.3 1059.25    18.6 1056.78    37.1 1053.31    55.7  1050.9
    92.8 1048.43   159.5 1046.43     218  1046.5   276.4 1045.22   325.1 1040.23
   490.6  1035.9     520 1036.14   534.2 1033.89   539.6 1032.66   549.4 1032.29
   560.1 1034.66   568.9 1037.33   617.9  1039.4   666.9 1043.45   696.2 1044.35
     706  1046.2   725.6 1057.21   735.4 1061.28   764.8 1069.29   784.4 1073.69
   813.8  1086.6   833.4 1097.37   843.2 1100.89     853  1105.4   872.5 1110.23
#Mann= 3 , 0 , 0
       0     .06       0   534.2    .045       0   560.1     .06       0
Bank Sta=534.2,560.1
XS Rating Curve= 0 ,0
Exp/Cntr=0.3,0.1

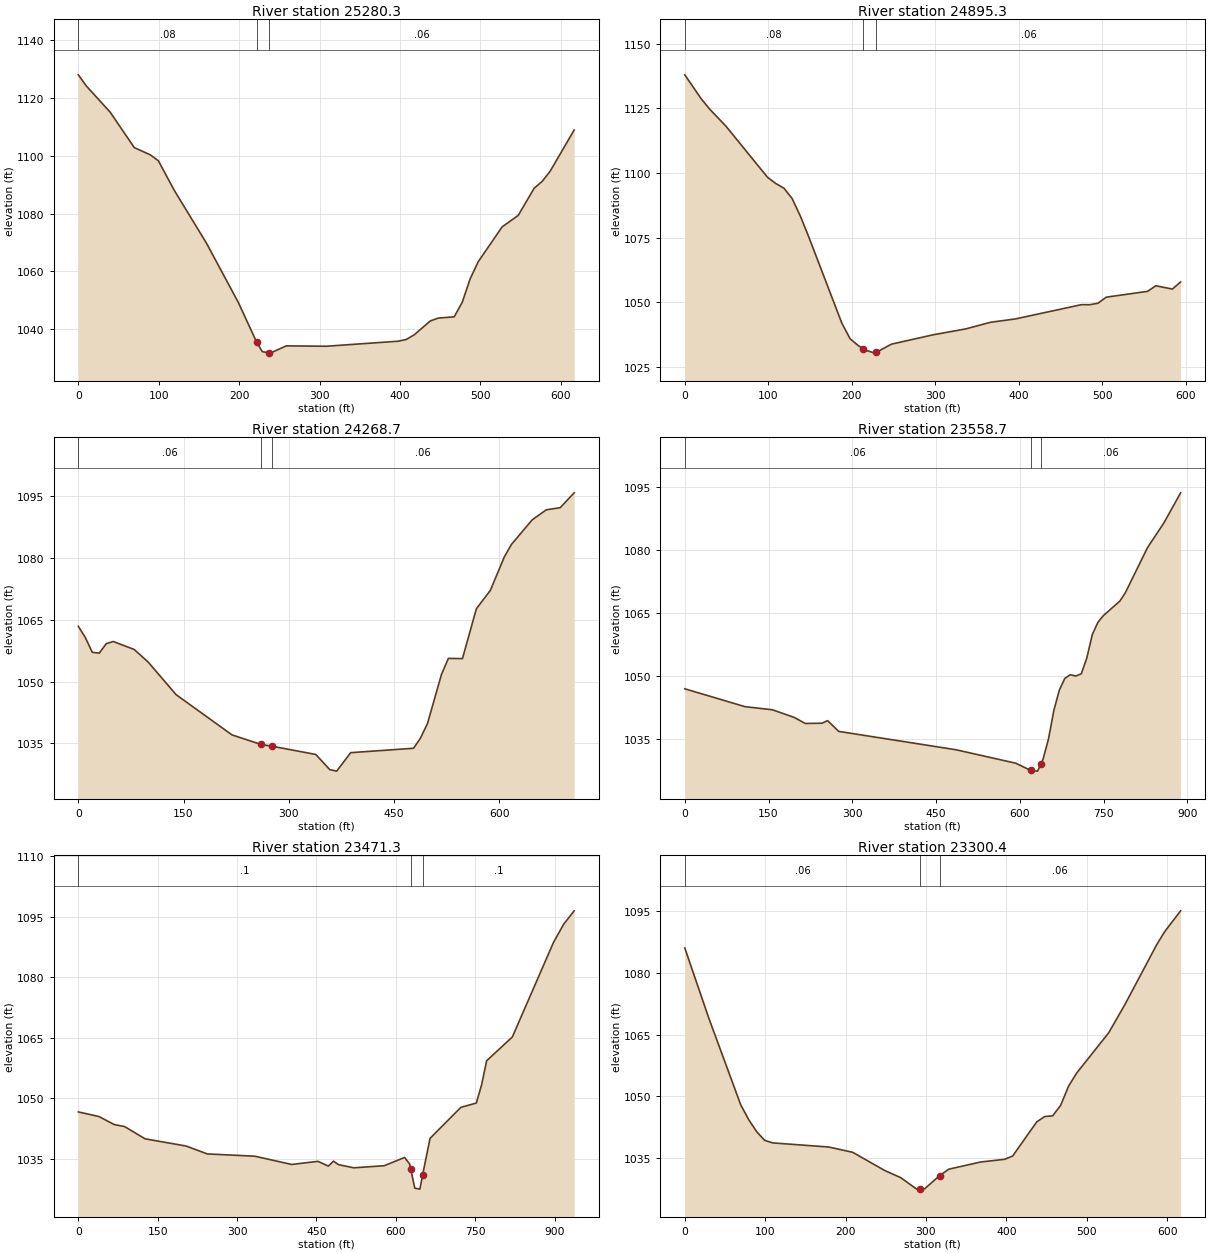
Type RM Length L Ch R = 1 ,25280.3 ,386,385.1,384.1
XS GIS Cut Line= 2
     1741832.619      425506.471     1742448.647      425536.091
#Sta/Elev= 30
       0    1128      10 1124.14    39.8 1115.02    69.6 1102.84    89.5 1100.33
    99.5  1098.3   119.4 1088.03   159.2 1069.87     199  1049.3   221.7 1035.63
   228.8 1032.29   236.8 1031.87   238.7 1031.77   258.6 1034.28   308.4 1034.15
   397.9 1035.89   407.8 1036.48   417.8 1038.11   437.7 1042.88   447.6 1043.88
   467.5 1044.33   477.5 1049.35   487.4 1057.49   497.4 1063.39   527.2 1075.45
   547.1 1079.38     567  1088.8     577 1091.18   586.9  1094.7   616.7 1108.91
#Mann= 3 , 0 , 0
       0     .08       0   221.7    .045       0   236.8     .06       0
Bank Sta=221.7,236.8
XS Rating Curve= 0 ,0
Exp/Cntr=0.3,0.1

Type RM Length L Ch R = 1 ,24895.3 ,628.8,626.5,618.3
XS GIS Cut Line= 2
     1741794.674      425893.505     1742388.414      425897.486
#Sta/Elev= 30
       0 1138.02    19.8 1128.68    29.7 1124.78    49.5 1118.06      99 1098.39
   108.8 1095.99   118.8 1094.12   128.6  1090.1   138.5 1083.26   148.4 1075.34
     188 1041.96   197.9  1035.9   207.8 1033.18   213.9 1032.03   217.7 1031.32
   227.6 1030.29   229.1 1030.54   247.4 1033.76   296.9 1037.35   336.5 1039.67
   366.2 1042.23   395.8 1043.52     475 1049.05   484.9 1049.03   494.8 1049.61
   504.7 1051.95   554.2  1054.2   564.1 1056.36   583.9 1055.09   593.8 1057.84
#Mann= 3 , 0 , 0
       0     .08       0   213.9    .045       0   229.1     .06       0
Bank Sta=213.9,229.1
XS Rating Curve= 0 ,0
Exp/Cntr=0.3,0.1

Type RM Length L Ch R = 1 ,24268.7 ,695.5,710,722.6
XS GIS Cut Line= 2
     1741767.863      426400.858     1742463.823      426276.525
#Sta/Elev= 30
       0 1063.45      10 1060.72    19.9 1057.13    29.9 1056.94    39.8 1059.23
    49.8 1059.76    79.7 1057.82    99.6 1054.76   139.4 1046.85   219.1 1037.08
   260.6 1034.75   275.8 1034.34   338.6 1032.33   358.5 1028.65   368.4 1028.28
   388.3 1032.76     478 1033.83   487.9 1036.31   497.9 1039.86   517.8 1051.76
   527.7 1055.66   547.7  1055.6   567.6 1067.72   587.5 1072.17   607.4 1080.29
   617.4 1083.29   647.2 1089.31   667.2 1091.73   687.1 1092.26     707 1095.86
#Mann= 3 , 0 , 0
       0     .06       0   260.6    .045       0   275.8     .06       0
Bank Sta=260.6,275.8
XS Rating Curve= 0 ,0
Exp/Cntr=0.3,0.1

Type RM Length L Ch R = 1 ,23558.7 ,83.5,87.4,89.8
XS GIS Cut Line= 5
     1741687.074      426805.956     1741898.293      426849.331
     1742177.405      426831.415     1742360.996      426896.677
     1742557.989      426912.049
#Sta/Elev= 30
       0 1047.05   107.8  1042.8   156.8 1042.06     196 1040.24   215.6 1038.81
   245.6 1038.86   255.6 1039.48   275.6 1036.92   485.3 1032.56   592.7 1029.35
   619.4 1027.64   631.7 1027.47   637.3 1029.09   641.4 1030.28   651.2 1035.11
   660.9 1041.96   670.7 1046.76   680.4 1049.51   690.2  1050.4     700 1050.08
   709.9 1050.61   719.8 1054.37   729.7 1059.95   739.6 1062.82   749.4 1064.44
   779.1 1067.92     789 1069.94   828.5 1080.62   858.1 1086.55   887.8 1093.65
#Mann= 3 , 0 , 0
       0     .06       0   619.4    .045       0   637.3     .06       0
Bank Sta=619.4,637.3
XS Rating Curve= 0 ,0
Exp/Cntr=0.3,0.1

Type RM Length L Ch R = 1 ,23471.3 ,188.7,171,154.5
XS GIS Cut Line= 5
     1741686.561      426886.562     1741900.179      426886.106
     1742149.116      426871.019     1742322.618        426973.8
     1742593.724      427000.326
#Sta/Elev= 30
       0 1046.61    38.8 1045.48      68 1043.48    87.4 1042.99   126.2 1039.95
   203.9 1038.16   243.6 1036.21   333.3 1035.65   403.2  1033.6     453 1034.37
   472.6 1033.19   482.2 1034.42   491.8 1033.55   520.6 1032.77   578.2 1033.29
   616.7 1035.34   626.3 1033.68   628.4 1032.38   635.9 1027.74   645.5 1027.49
   650.8 1031.07   664.7 1040.06     723 1047.75   752.2 1048.81     762 1053.24
   771.7 1059.28   820.3 1065.18   898.2 1088.64   917.6 1093.17   937.1 1096.42
#Mann= 3 , 0 , 0
       0      .1       0   628.4    .045       0   650.8      .1       0
Bank Sta=628.4,650.8
XS Rating Curve= 0 ,0
Exp/Cntr=0.3,0.1

Type RM Length L Ch R = 1 ,23300.4 ,402.1,408.3,414.3
XS GIS Cut Line= 2
     1742016.172       427195.55     1742618.999      427064.886
#Sta/Elev= 30
       0  1086.1    29.8 1069.09    69.6 1047.96    79.6 1044.34    89.5 1041.41
    99.5 1039.31   109.4 1038.71   179.1 1037.71   208.9 1036.42   248.7    1032
   268.6 1030.26   288.5 1027.47   293.1 1027.52   298.5 1027.58   317.1 1030.77
   328.3 1032.31   368.1 1034.07     398 1034.72   407.9 1035.53   437.8 1043.82
   447.7 1045.12   457.6 1045.29   467.6 1047.86   477.5 1052.55   487.5  1055.7
   527.3 1065.48   547.2 1072.24     587 1086.89   596.9 1090.06   616.8 1095.14
#Mann= 3 , 0 , 0
       0     .06       0   293.1    .045       0   317.1     .06       0
Bank Sta=293.1,317.1
XS Rating Curve= 0 ,0
Exp/Cntr=0.3,0.1

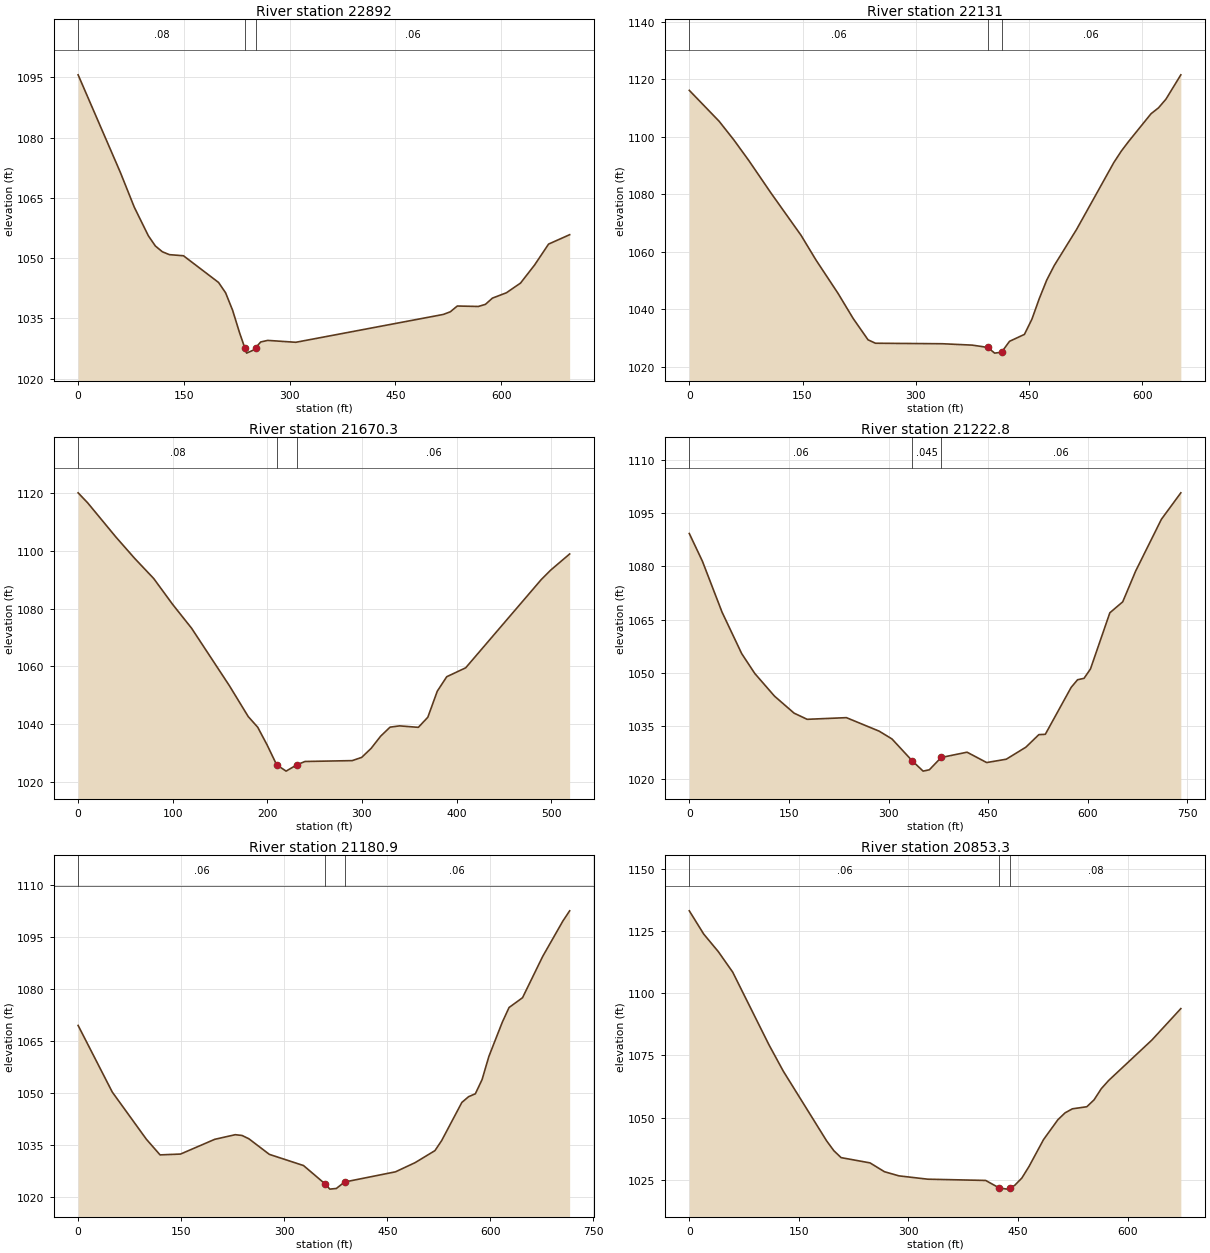
Type RM Length L Ch R = 1 ,22892   ,754,761.1,764.9
XS GIS Cut Line= 2
     1742081.712      427522.476     1742777.665      427563.775
#Sta/Elev= 30
       0 1095.63    59.8 1071.38    79.7 1062.66    99.6 1055.56   109.6    1053
   119.5 1051.57   129.5 1050.85   149.4 1050.58   199.2 1043.93   209.2 1041.35
   219.1 1037.02   229.1 1031.35   236.7  1027.5     239 1026.33     249 1027.12
   251.9  1027.7     259 1029.11   268.9  1029.5   308.8 1029.03   517.9 1035.96
   527.9 1036.62   537.8 1038.06   567.7 1037.95   577.7 1038.47   587.6 1040.02
   607.5 1041.36   627.5 1043.77   647.4 1048.26   667.3 1053.48   697.2 1055.82
#Mann= 3 , 0 , 0
       0     .08       0   236.7    .045       0   251.9     .06       0
Bank Sta=236.7,251.9
XS Rating Curve= 0 ,0
Exp/Cntr=0.3,0.1

Type RM Length L Ch R = 1 ,22131   ,461.8,460.7,455.3
XS GIS Cut Line= 2
        1742077.      427813.978     1742688.137      428038.509
#Sta/Elev= 30
       0 1116.16    39.5 1105.42    59.2 1098.87    78.9 1091.74   108.5 1080.36
     148 1065.78   167.7 1057.23   197.3 1045.47     217 1036.88   236.8 1029.43
   246.6 1028.25   335.4 1028.07   374.9 1027.59   395.2  1026.8   404.5 1024.81
   413.6 1025.13   424.2 1028.92   443.9 1031.32   453.8 1036.59   463.6 1043.77
   473.5 1050.23   483.4 1055.26     513 1067.82   562.3 1091.05   572.2 1095.03
     582 1098.42   611.6 1108.03   621.5 1110.08   631.4 1113.11   651.1 1121.56
#Mann= 3 , 0 , 0
       0     .06       0   395.2    .045       0   413.6     .06       0
Bank Sta=395.2,413.6
XS Rating Curve= 0 ,0
Exp/Cntr=0.3,0.1

Type RM Length L Ch R = 1 ,21670.3 ,472.8,447.5,418.2
XS GIS Cut Line= 2
     1742027.342      428233.591     1742538.317      428327.246
#Sta/Elev= 30
       0 1120.16      10 1116.73      40 1104.82    59.9  1097.4    79.9 1090.47
    99.9 1081.51   119.9 1073.26   159.8 1053.38   179.8 1042.64   189.8 1038.96
   199.8 1032.78   209.8 1025.95   210.7 1025.75   219.8 1023.74   231.6    1026
   239.8 1027.08   289.7 1027.38   299.7  1028.5   309.7 1031.63   319.7 1035.83
   329.7 1038.98   339.7 1039.42   359.6 1038.91   369.6 1042.41   379.6 1051.44
   389.6 1056.45   409.6 1059.53   489.5 1090.11   499.5 1093.39   519.5 1098.98
#Mann= 3 , 0 , 0
       0     .08       0   210.7    .045       0   231.6     .06       0
Bank Sta=210.7,231.6
XS Rating Curve= 0 ,0
Exp/Cntr=0.3,0.1

Type RM Length L Ch R = 1 ,21222.8 ,46.9,41.9,36.9
XS GIS Cut Line= 5
     1742008.419      428922.438     1742190.497       428689.35
     1742260.278      428600.922     1742307.856       428503.66
     1742528.558      428468.522
#Sta/Elev= 30
       0 1089.29    19.7 1081.49    49.3 1067.11    78.9  1055.4    98.6  1049.8
   128.2 1043.42   157.8  1038.6   177.5 1036.86   236.6 1037.33   285.9 1033.52
   305.2 1031.32   335.9 1025.11   352.1 1022.24   361.5 1022.62   379.3 1026.09
   418.3 1027.58   447.8 1024.66   477.3  1025.6   506.8 1028.99   526.4 1032.54
   536.1 1032.63     575 1045.86   584.7 1048.03   594.4 1048.42   604.1 1051.06
   633.3 1066.92   652.7 1070.02   672.2 1078.71     711 1093.33   740.2 1100.77
#Mann= 3 , 0 , 0
       0     .06       0   335.9    .045       0   379.3     .06       0
Bank Sta=335.9,379.3
XS Rating Curve= 0 ,0
Exp/Cntr=0.3,0.1

Type RM Length L Ch R = 1 ,21180.9 ,305.8,327.5,348.9
XS GIS Cut Line= 4
      1742056.33      428965.394     1742248.534      428699.468
     1742331.233      428526.982     1742526.811      428512.205
#Sta/Elev= 30
       0  1069.5    49.7  1050.3    99.4 1036.68   119.3 1032.18   149.1 1032.42
   198.9 1036.67   228.7    1038   238.6 1037.78   248.6 1036.82   278.4 1032.33
   328.1 1029.11   359.9 1023.75   366.4 1022.31   375.9  1022.5   387.9 1024.36
     462  1027.3   490.7 1029.96   519.4 1033.41   529.2 1036.31   558.6 1047.31
   568.4 1048.96   578.2 1049.79     588 1053.88   597.9 1060.56   617.5 1070.45
   627.3 1074.67   646.9 1077.49   676.3 1089.41   705.7 1099.62   715.5 1102.54
#Mann= 3 , 0 , 0
       0     .06       0   359.9    .045       0   387.9     .06       0
Bank Sta=359.9,387.9
XS Rating Curve= 0 ,0
Exp/Cntr=0.3,0.1

Type RM Length L Ch R = 1 ,20853.3 ,474.6,464.3,453.6
XS GIS Cut Line= 2
     1741944.387      429015.956     1742606.082      428893.876
#Sta/Elev= 30
       0 1133.04    19.8 1123.68    39.6 1116.69    59.4 1108.42   108.8 1079.36
   128.6 1068.66     188 1040.62   197.9 1036.66   207.8 1033.89   247.4 1031.77
   267.2 1028.22     287 1026.56   326.5 1025.22   405.7 1024.72   424.5 1021.67
   435.4 1021.23   439.7 1021.87   445.3  1022.7   455.2 1025.66   465.1 1030.35
   484.9 1041.12   504.6 1049.12   514.5 1051.89   524.4 1053.49   544.2 1054.33
   554.1  1057.1     564 1061.58   573.9 1064.83   633.3 1081.14   672.9 1093.76
#Mann= 3 , 0 , 0
       0     .06       0   424.5    .045       0   439.7     .08       0
Bank Sta=424.5,439.7
XS Rating Curve= 0 ,0
Exp/Cntr=0.3,0.1

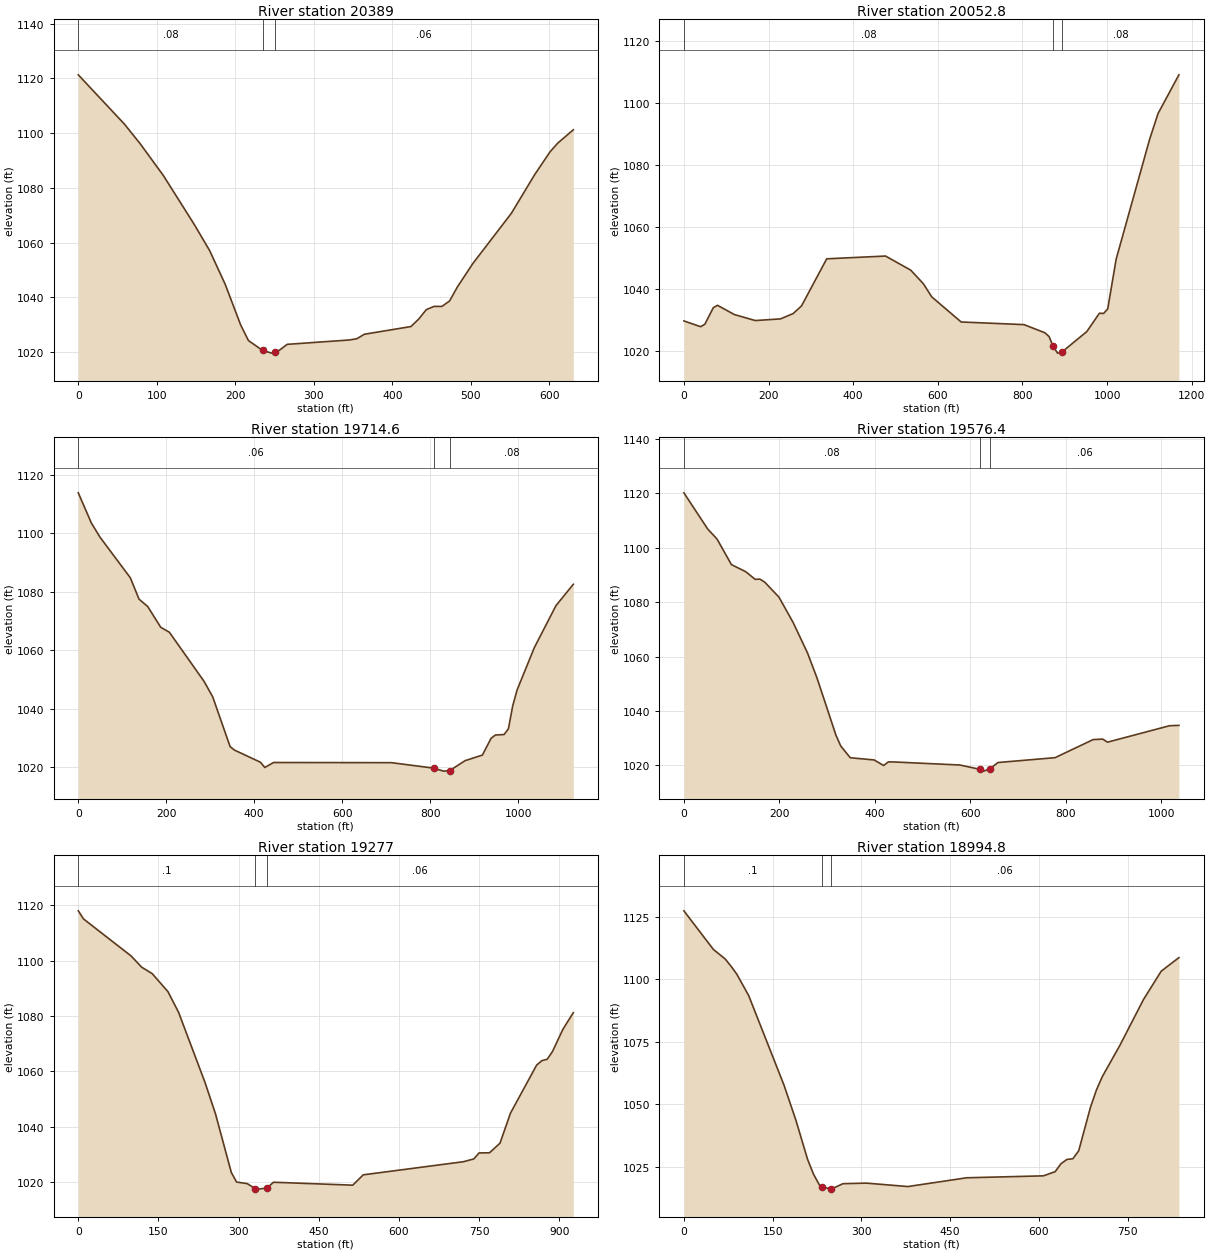
Type RM Length L Ch R = 1 ,20389   ,340.9,336.2,331.5
XS GIS Cut Line= 2
     1742332.793      429471.656     1742839.726       429096.92
#Sta/Elev= 30
       0 1121.34    59.1 1103.21    78.8 1096.15   108.4 1084.49   147.8 1066.57
   167.4    1057   187.2 1044.66   206.8 1029.86   216.7 1024.16   234.6 1020.58
   246.2 1019.57   250.5 1020.03   256.1 1020.62     266 1022.78   344.8 1024.37
   354.6 1024.82   364.4 1026.48   423.6 1029.29   433.4 1031.99   443.2 1035.48
   453.1 1036.66     463 1036.65   472.8 1038.64   482.6  1043.7   502.4 1052.32
   551.6 1070.74   581.2 1084.85   600.8  1093.2   610.7  1096.4   630.4 1101.24
#Mann= 3 , 0 , 0
       0     .08       0   234.6    .045       0   250.5     .06       0
Bank Sta=234.6,250.5
XS Rating Curve= 0 ,0
Exp/Cntr=0.3,0.1

Type RM Length L Ch R = 1 ,20052.8 ,347.7,338.3,322.9
XS GIS Cut Line= 3
     1742064.276      429997.952     1742695.354      429622.003
     1742979.197      429292.066
#Sta/Elev= 30
       0 1029.83    39.7 1027.97    49.6 1028.78    69.5 1034.09    79.4 1034.87
   119.1 1031.89   168.8 1029.95   228.3 1030.49   258.1 1032.19     278 1034.67
   337.5 1049.83   476.5 1050.73     536 1046.19   565.8 1041.83   585.7 1037.58
   655.2 1029.49   803.8 1028.64   853.3    1026   863.2 1024.76   871.7 1021.84
     883 1019.46   893.2  1019.8   952.2 1026.41   981.9 1032.31   991.8 1032.24
  1001.6 1033.71  1021.4 1049.68  1100.6 1088.33  1120.4  1096.6  1169.8 1109.09
#Mann= 3 , 0 , 0
       0     .08       0   871.7    .045       0   893.2     .08       0
Bank Sta=871.7,893.2
XS Rating Curve= 0 ,0
Exp/Cntr=0.3,0.1

Type RM Length L Ch R = 1 ,19714.6 ,144.2,138.2,159.4
XS GIS Cut Line= 4
     1742311.735      430355.717     1742577.272      430025.097
     1742731.636      429830.111      1743143.95      429643.061
#Sta/Elev= 30
       0 1113.81    29.6 1103.53    49.3 1098.66   118.3 1084.76   138.1 1077.45
   157.8 1074.94   187.4 1067.84   207.1 1066.13     286 1049.33   305.7 1044.01
   345.2 1027.02     355 1025.84   414.2 1021.68     424 1019.89     444 1021.59
   712.1 1021.53   807.9 1019.67   830.2 1018.64   844.2  1018.8   879.4 1022.22
   918.8 1024.13   938.5 1029.86   948.3 1030.99     968 1031.15   977.9  1033.1
   987.7 1040.96   997.6 1046.37  1036.9 1060.89  1086.1 1075.25  1125.5 1082.54
#Mann= 3 , 0 , 0
       0     .06       0   807.9    .045       0   844.2     .08       0
Bank Sta=807.9,844.2
XS Rating Curve= 0 ,0
Exp/Cntr=0.3,0.1

Type RM Length L Ch R = 1 ,19576.4 ,287.6,299.4,293.6
XS GIS Cut Line= 4
     1742402.877      430369.992     1742639.821      430074.974
     1742782.332       429894.96      1743172.89       429717.78
#Sta/Elev= 30
       0 1120.19    49.8 1106.92    69.7 1103.14    99.6 1093.81   129.4 1091.22
   149.4 1088.39   159.3 1088.48   169.3 1087.37   199.2 1081.84     229 1072.47
   258.9 1061.36   278.8 1052.16   318.6 1031.07   328.6 1027.14   348.5 1022.84
   398.4 1022.03   418.3    1020   428.3 1021.31   438.3  1021.3     578 1020.17
   620.1 1018.58   627.9 1017.92   641.4 1018.82   657.8 1021.08   777.5 1022.87
   857.3 1029.52   877.3 1029.68   887.2 1028.56  1016.9 1034.59  1036.8 1034.74
#Mann= 3 , 0 , 0
       0     .08       0   620.1    .045       0   641.4     .06       0
Bank Sta=620.1,641.4
XS Rating Curve= 0 ,0
Exp/Cntr=0.3,0.1

Type RM Length L Ch R = 1 ,19277   ,269.9,282.1,289.5
XS GIS Cut Line= 3
      1742458.89      430373.493     1742999.438       429991.78
     1743260.286      429947.194
#Sta/Elev= 30
       0 1117.98     9.9 1115.03    98.8 1101.67   118.5 1097.62   138.3 1095.28
   167.9 1088.73   187.7 1081.28     237 1056.01   256.8 1044.55   286.4 1023.36
   296.3 1019.91     316 1019.36   330.9 1017.58   335.8 1017.36   352.7 1017.73
   365.4 1019.85   513.6 1018.79   533.3 1022.53   720.5 1027.26   740.2 1028.28
     750 1030.45   769.6  1030.5   789.2 1033.98   808.8 1044.84   857.8 1062.22
   867.6 1063.82   877.4  1064.3   887.2 1067.04   906.8 1075.11   926.4 1081.17
#Mann= 3 , 0 , 0
       0      .1       0   330.9    .045       0   352.7     .06       0
Bank Sta=330.9,352.7
XS Rating Curve= 0 ,0
Exp/Cntr=0.3,0.1

Type RM Length L Ch R = 1 ,18994.8 ,449,444.6,439.6
XS GIS Cut Line= 2
     1742643.244      430519.553     1743388.046      430137.904
#Sta/Elev= 30
       0 1127.34    49.8 1111.92    69.7 1108.11    79.7 1105.19    89.7 1101.92
   109.6 1093.42   169.4 1057.53   189.3 1043.66   209.2 1027.89   219.2 1021.98
   229.2 1017.65     234 1016.92     249 1016.03     269 1018.21   308.8 1018.43
   378.6 1017.06   478.2 1020.57   607.7 1021.34   627.7 1023.02   637.6 1026.21
   647.6  1027.9   657.6 1028.18   667.5 1031.38   687.4 1048.79   697.4 1055.65
   707.4 1061.03   737.3 1073.62   777.1 1091.91     807 1103.21   836.9 1108.63
#Mann= 3 , 0 , 0
       0      .1       0     234    .045       0     249     .06       0
Bank Sta=234,249
XS Rating Curve= 0 ,0
Exp/Cntr=0.3,0.1

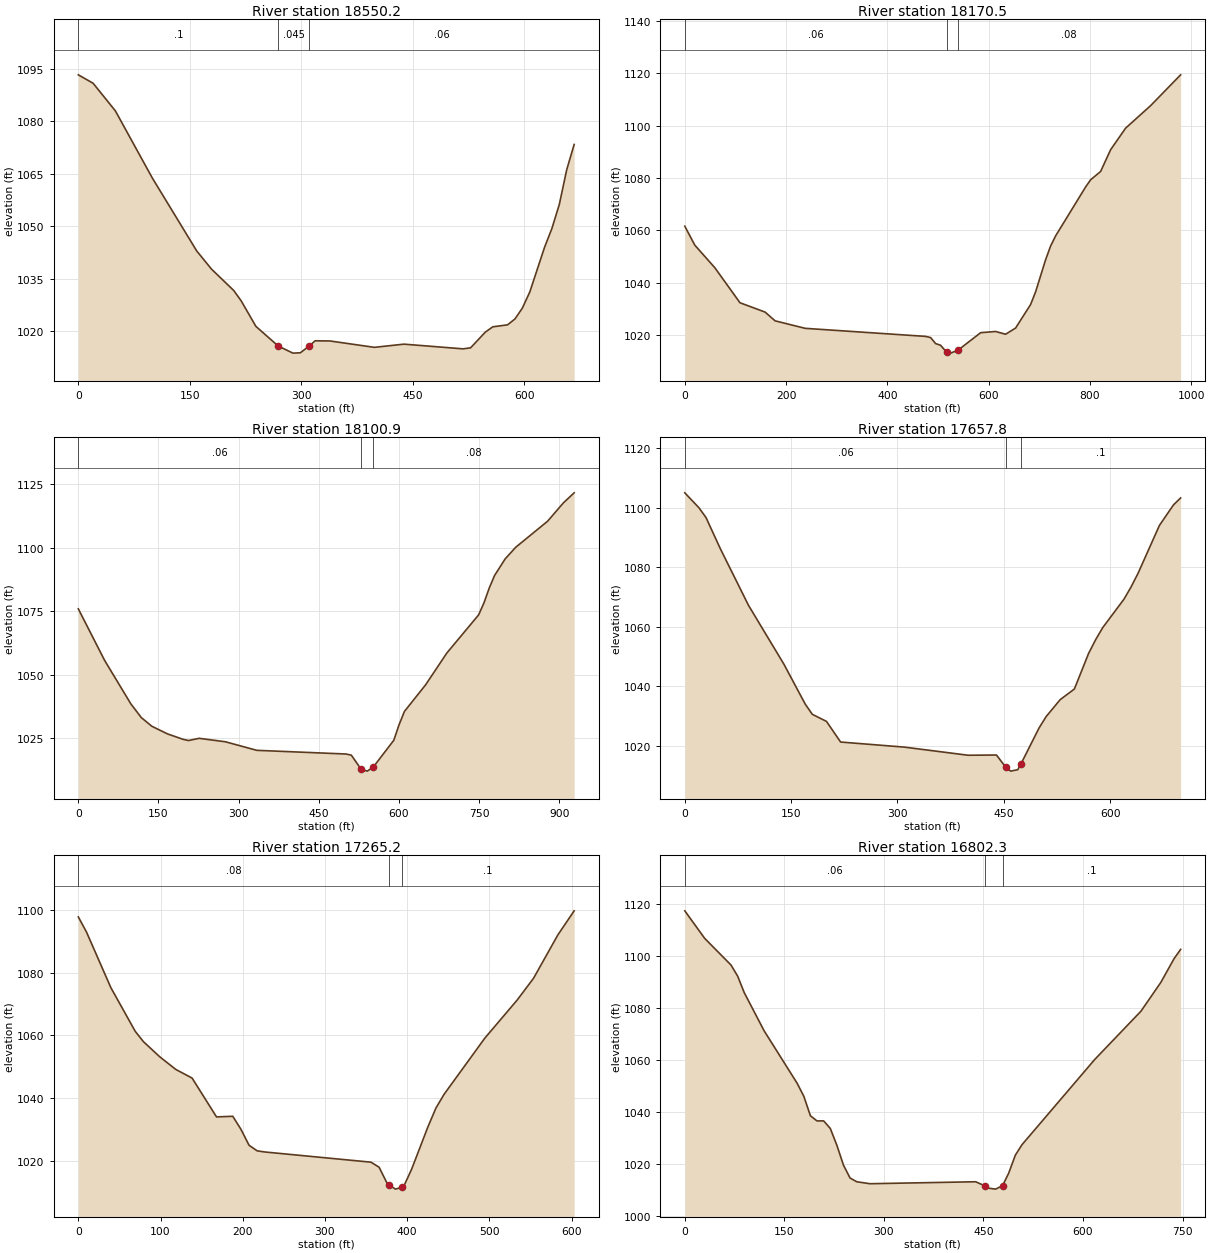
Type RM Length L Ch R = 1 ,18550.2 ,397.5,379.7,358.6
XS GIS Cut Line= 2
     1742941.302      430871.332     1743463.941      430457.243
#Sta/Elev= 30
       0 1093.21    19.9  1090.8    49.8 1082.93    99.5 1063.77   159.2 1042.96
   179.1 1037.77     209 1031.67     219 1028.72   238.8 1021.43   268.8 1015.83
   288.6  1013.8   298.6  1013.9   310.5 1015.85   318.5 1017.32   338.4 1017.27
   398.1 1015.45   437.9 1016.36   517.5 1015.02   527.5 1015.31   547.4  1019.8
   557.3  1021.3   577.2 1021.87   587.2 1023.55   597.1 1026.63   607.1 1031.23
     627    1044   636.9 1049.38   646.9 1056.28   656.8 1066.14   666.8 1073.34
#Mann= 3 , 0 , 0
       0      .1       0   268.8    .045       0   310.5     .06       0
Bank Sta=268.8,310.5
XS Rating Curve= 0 ,0
Exp/Cntr=0.3,0.1

Type RM Length L Ch R = 1 ,18170.5 ,69.4,69.6,69.4
XS GIS Cut Line= 3
     1743382.851        431292.5     1743475.945      430816.004
     1743514.761      430323.752
#Sta/Elev= 30
       0 1061.53    19.8 1054.29    59.4 1045.64     109 1032.26   158.5  1028.7
   178.4 1025.34   237.8 1022.48   475.6  1019.4   485.5 1018.95   495.4 1016.65
   505.3    1016   516.9 1013.39     525    1013   539.4 1014.09   584.3 1020.81
   613.9 1021.28   633.6 1020.22   653.4  1022.6     683 1031.59   692.9 1036.44
   712.6 1048.69   722.5 1053.95   732.4 1057.83   791.6 1076.52   801.5 1079.28
   821.3 1082.46     841 1090.77   870.6 1099.02     920 1107.63   979.3 1119.42
#Mann= 3 , 0 , 0
       0     .06       0   516.9    .045       0   539.4     .08       0
Bank Sta=516.9,539.4
XS Rating Curve= 0 ,0
Exp/Cntr=0.3,0.1

Type RM Length L Ch R = 1 ,18100.9 ,432.8,443.1,453
XS GIS Cut Line= 3
      1743444.18      431328.966     1743542.143      430827.548
     1743574.913      430411.975
#Sta/Elev= 30
       0 1075.94    49.1 1055.71    98.2 1038.59   117.9 1033.16   137.6 1029.76
     167 1026.74   196.5 1024.59   206.3 1024.15     226 1025.02   275.1 1023.66
     334 1020.29   501.1 1018.84   510.9 1018.38   529.2 1012.84   540.7 1012.11
   551.9 1013.71   590.3 1024.24   600.2 1030.38   610.2 1035.59   649.8 1046.05
   689.6 1058.58   749.1 1073.59     759 1078.28     769 1084.19   778.9 1089.07
   798.7  1095.6   818.6  1100.2   878.1 1110.42   907.9  1117.7   927.8 1121.59
#Mann= 3 , 0 , 0
       0     .06       0   529.2    .045       0   551.9     .08       0
Bank Sta=529.2,551.9
XS Rating Curve= 0 ,0
Exp/Cntr=0.3,0.1

Type RM Length L Ch R = 1 ,17657.8 ,388,392.7,397.3
XS GIS Cut Line= 2
     1743675.034      431453.895     1744024.468      430847.894
#Sta/Elev= 30
       0    1105      20 1099.98      30 1096.67      50  1086.3    89.9 1067.21
   139.9 1047.43   169.9 1034.06   179.9 1030.63   199.9 1028.25   219.8 1021.32
   309.8 1019.61   399.7 1016.88   439.7 1016.96   452.9 1012.81   459.7 1011.55
   469.7 1012.02   474.5 1014.09   499.7    1026   509.7 1029.84   529.6 1035.56
   549.6 1039.12   569.6 1051.03   579.6 1055.68   589.6 1059.74   619.6  1069.3
   629.6 1073.39   639.6 1078.05   669.6 1094.06   689.5 1100.97   699.5 1103.28
#Mann= 3 , 0 , 0
       0     .06       0   452.9    .045       0   474.5      .1       0
Bank Sta=452.9,474.5
XS Rating Curve= 0 ,0
Exp/Cntr=0.3,0.1

Type RM Length L Ch R = 1 ,17265.2 ,453.6,462.9,466.2
XS GIS Cut Line= 2
     1743974.042       431560.01     1744375.897      431110.137
#Sta/Elev= 30
       0 1097.77     9.9 1092.97    39.6 1075.19    69.2 1061.28    79.1    1058
    98.9 1053.17   118.7 1049.08   138.4 1046.35   168.1 1033.96   187.9 1034.15
   197.8 1030.02   207.7 1024.91   217.6 1023.12   227.4 1022.75     356 1019.51
   365.9  1017.9   375.8 1012.69   378.5  1012.2   385.7 1010.91   393.5 1011.49
   395.6 1011.65   405.4 1017.22   425.2 1030.72   435.1 1036.82     445 1041.18
   494.4 1059.05     534 1071.29   553.8  1078.2   583.4 1092.04   603.2 1099.72
#Mann= 3 , 0 , 0
       0     .08       0   378.5    .045       0   393.5      .1       0
Bank Sta=378.5,393.5
XS Rating Curve= 0 ,0
Exp/Cntr=0.3,0.1

Type RM Length L Ch R = 1 ,16802.3 ,458.8,467.6,476.2
XS GIS Cut Line= 2
     1744134.554      431867.263     1744766.448      431468.705
#Sta/Elev= 30
       0 1117.44    29.9 1106.85    69.7 1096.54    79.7 1092.26    89.6 1085.91
   119.5 1071.24   169.3 1051.01   179.3 1046.04   189.3  1038.5   199.2 1036.51
   209.2 1036.53   219.2 1033.63   229.1 1027.16   239.1 1019.48     249 1014.52
     259 1013.09   278.9 1012.32   438.3 1013.08   452.8 1011.42   458.2  1010.6
   468.2 1010.24   478.8 1011.55   488.1 1016.43   498.1 1023.34     508 1027.33
   617.6 1060.16   687.3 1078.77   717.2 1089.84   737.1 1098.96   747.1 1102.59
#Mann= 3 , 0 , 0
       0     .06       0   452.8    .045       0   478.8      .1       0
Bank Sta=452.8,478.8
XS Rating Curve= 0 ,0
Exp/Cntr=0.3,0.1

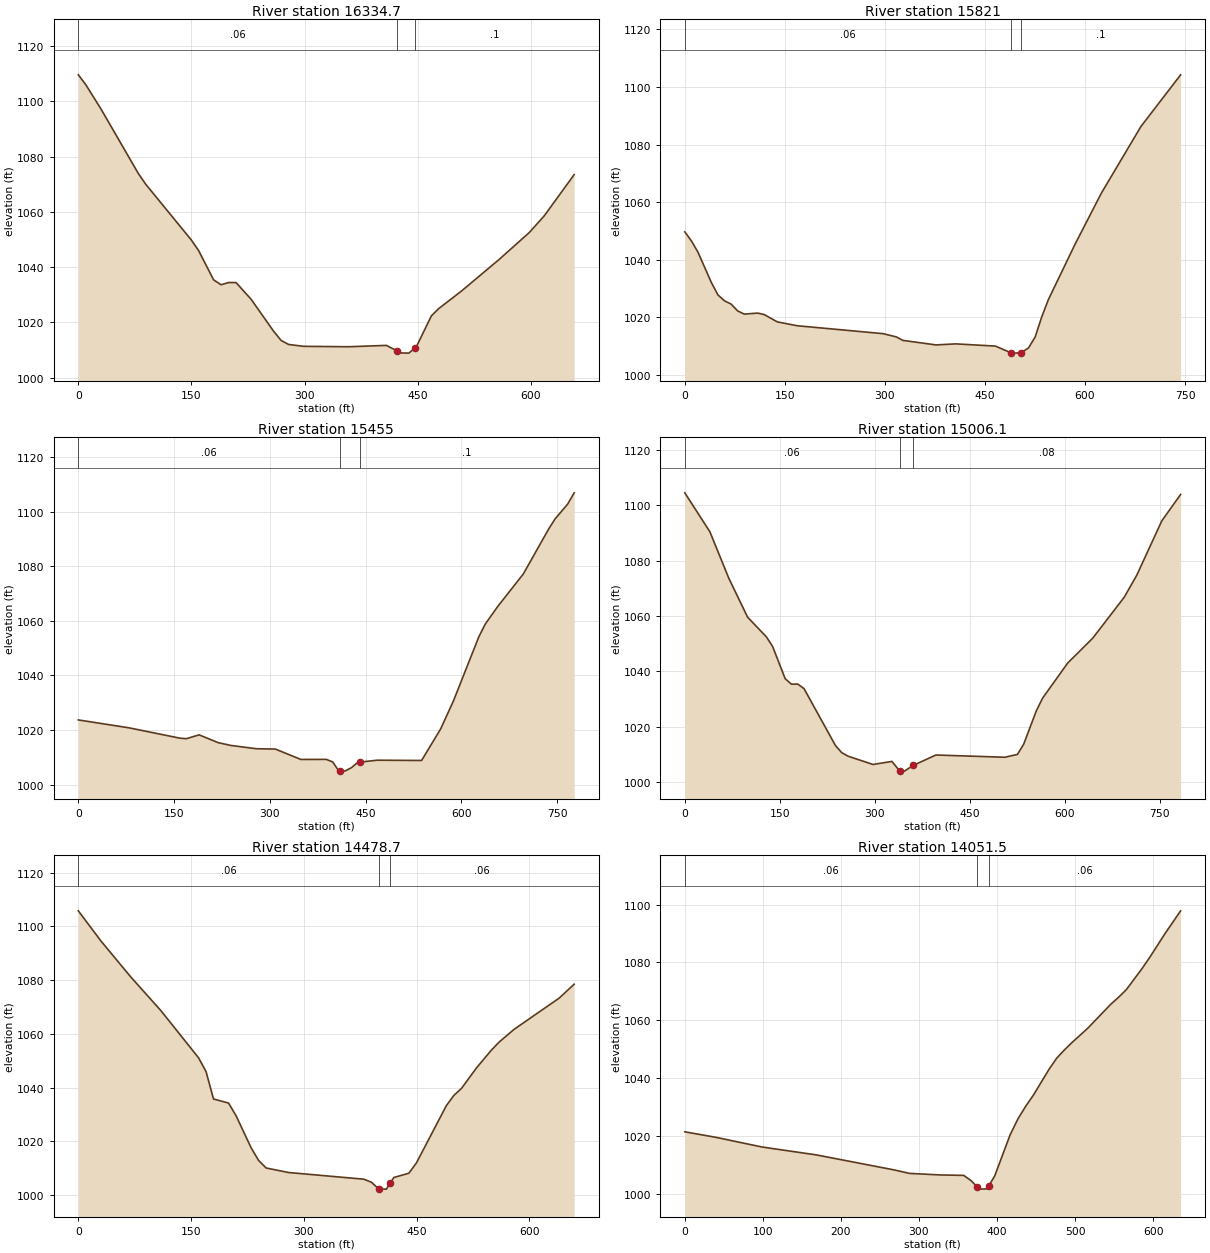
Type RM Length L Ch R = 1 ,16334.7 ,515.3,513.8,511.8
XS GIS Cut Line= 2
     1744240.405      432136.156      1744887.66      432019.671
#Sta/Elev= 30
       0 1109.57      10 1105.95    29.9 1097.27    79.7  1073.8    89.7 1069.86
   149.5 1049.92   159.4 1046.03   179.4 1035.37   189.3 1033.59   199.3 1034.39
   209.2 1034.38   229.2 1028.32   259.1 1016.73     269 1013.42     279 1011.97
   298.9  1011.3   358.7 1011.15   408.5 1011.64     422 1009.77   428.5  1008.9
   438.4 1008.84   446.3 1010.69   448.4 1011.18   468.3 1022.35   478.3 1025.03
   508.2 1031.32     558 1042.72   597.9 1052.44   617.8 1058.48   657.6 1073.44
#Mann= 3 , 0 , 0
       0     .06       0     422    .045       0   446.3      .1       0
Bank Sta=422,446.3
XS Rating Curve= 0 ,0
Exp/Cntr=0.3,0.1

Type RM Length L Ch R = 1 ,15821   ,363.8,366,368
XS GIS Cut Line= 2
     1744268.784      432664.518      1744989.32      432481.762
#Sta/Elev= 30
       0 1049.71     9.9 1046.58    19.8 1042.62    39.6 1032.24    49.6 1027.84
    59.5 1025.76    69.4 1024.63    79.3 1022.25    89.2 1021.14     109  1021.5
   118.9 1021.01   138.8 1018.44   168.5 1017.11   297.3 1014.36   317.2 1013.23
   327.1 1012.02   376.6 1010.45   406.4 1010.81   465.8 1010.04   489.5 1007.66
   495.6  1007.6   504.6 1007.76   515.4 1009.42   525.3  1013.2   535.2  1020.2
   545.1 1026.17   584.8 1045.26   624.4 1063.08   683.9 1086.29   743.4 1104.23
#Mann= 3 , 0 , 0
       0     .06       0   489.5    .045       0   504.6      .1       0
Bank Sta=489.5,504.6
XS Rating Curve= 0 ,0
Exp/Cntr=0.3,0.1

Type RM Length L Ch R = 1 ,15455   ,455.7,448.9,441
XS GIS Cut Line= 2
     1744345.784      432971.288     1745112.001      432843.483
#Sta/Elev= 30
       0 1023.73    79.7 1020.82   159.3 1017.04   169.3 1016.86   189.2 1018.26
   219.1 1015.41     239 1014.38   278.8 1013.18   308.7 1013.06   348.6 1009.26
   388.4 1009.28   398.4 1008.37   408.3 1004.98   409.6 1004.99   418.3 1005.07
   428.2 1006.29   438.2  1008.3     441 1008.27   468.1 1008.98   537.8 1008.88
   567.7 1020.46   587.6 1030.64   627.4 1054.13   637.4 1058.77   657.3 1065.34
   697.1 1077.15     737 1093.69   746.9 1097.32   766.8 1102.81   776.8 1106.88
#Mann= 3 , 0 , 0
       0     .06       0   409.6    .045       0     441      .1       0
Bank Sta=409.6,441
XS Rating Curve= 0 ,0
Exp/Cntr=0.3,0.1

Type RM Length L Ch R = 1 ,15006.1 ,529.8,527.3,525.1
XS GIS Cut Line= 2
     1744495.559      433419.141     1745195.953      433069.688
#Sta/Elev= 30
       0 1104.55    39.6 1090.47    69.4 1073.69    99.1 1059.58   128.8 1052.44
   138.7 1048.93   158.5 1037.29   168.4 1035.32   178.3 1035.37   188.2 1033.72
   237.8 1013.14   247.7 1010.56   257.6 1009.28   297.2 1006.28     327 1007.38
   339.2 1003.93   346.8 1003.87   360.3 1005.91   396.3  1009.7   505.3 1008.89
   525.1 1009.92     535 1013.63   554.8 1025.61   564.8 1030.28   604.4 1042.96
     644 1051.98   693.6 1066.75   713.4 1074.71     753 1094.41   782.7 1103.97
#Mann= 3 , 0 , 0
       0     .06       0   339.2    .045       0   360.3     .08       0
Bank Sta=339.2,360.3
XS Rating Curve= 0 ,0
Exp/Cntr=0.3,0.1

Type RM Length L Ch R = 1 ,14478.7 ,427.6,427.3,426.9
XS GIS Cut Line= 2
     1744845.664      433772.931     1745395.336      433408.574
#Sta/Elev= 30
       0 1105.78      30 1094.58    69.9 1081.12   109.9  1068.6   159.9 1051.07
   169.9 1045.92   179.8 1035.73   199.8 1034.22   209.8 1029.51   229.8 1017.59
   239.8 1012.85   249.8 1010.05   279.8 1008.36   379.7 1005.88   389.7 1004.77
   399.8 1002.21   409.7 1002.18   414.8 1004.39   419.7 1006.52   439.6 1008.09
   449.6 1011.89   489.6  1033.3   499.6  1037.1   509.6 1039.66   529.6 1047.31
   549.6 1053.98   559.6 1056.89   579.5 1061.64   639.5 1073.27   659.5 1078.47
#Mann= 3 , 0 , 0
       0     .06       0   399.8    .045       0   414.8     .06       0
Bank Sta=399.8,414.8
XS Rating Curve= 0 ,0
Exp/Cntr=0.3,0.1

Type RM Length L Ch R = 1 ,14051.5 ,630.2,621.9,613.2
XS GIS Cut Line= 2
     1745140.581      434070.953     1745665.771       433713.68
#Sta/Elev= 30
       0 1021.44    39.7 1019.54    99.2 1016.18   168.7 1013.45     268 1008.28
   287.8 1007.07   327.5 1006.53   357.3 1006.38   367.2 1004.47   374.6 1002.35
   377.1 1001.63   387.1 1001.71   389.6 1002.84     397 1006.17   416.8 1020.41
   426.8 1025.91   436.7 1030.26   446.6 1034.12   466.5 1042.99   476.4 1046.88
   486.3 1049.74   496.2 1052.34   516.1  1057.2   545.9 1065.58   555.8 1067.96
   565.7 1070.59   585.6  1077.8   595.5 1081.68   615.3 1089.99   635.2 1097.82
#Mann= 3 , 0 , 0
       0     .06       0   374.6    .045       0   389.6     .06       0
Bank Sta=374.6,389.6
XS Rating Curve= 0 ,0
Exp/Cntr=0.3,0.1