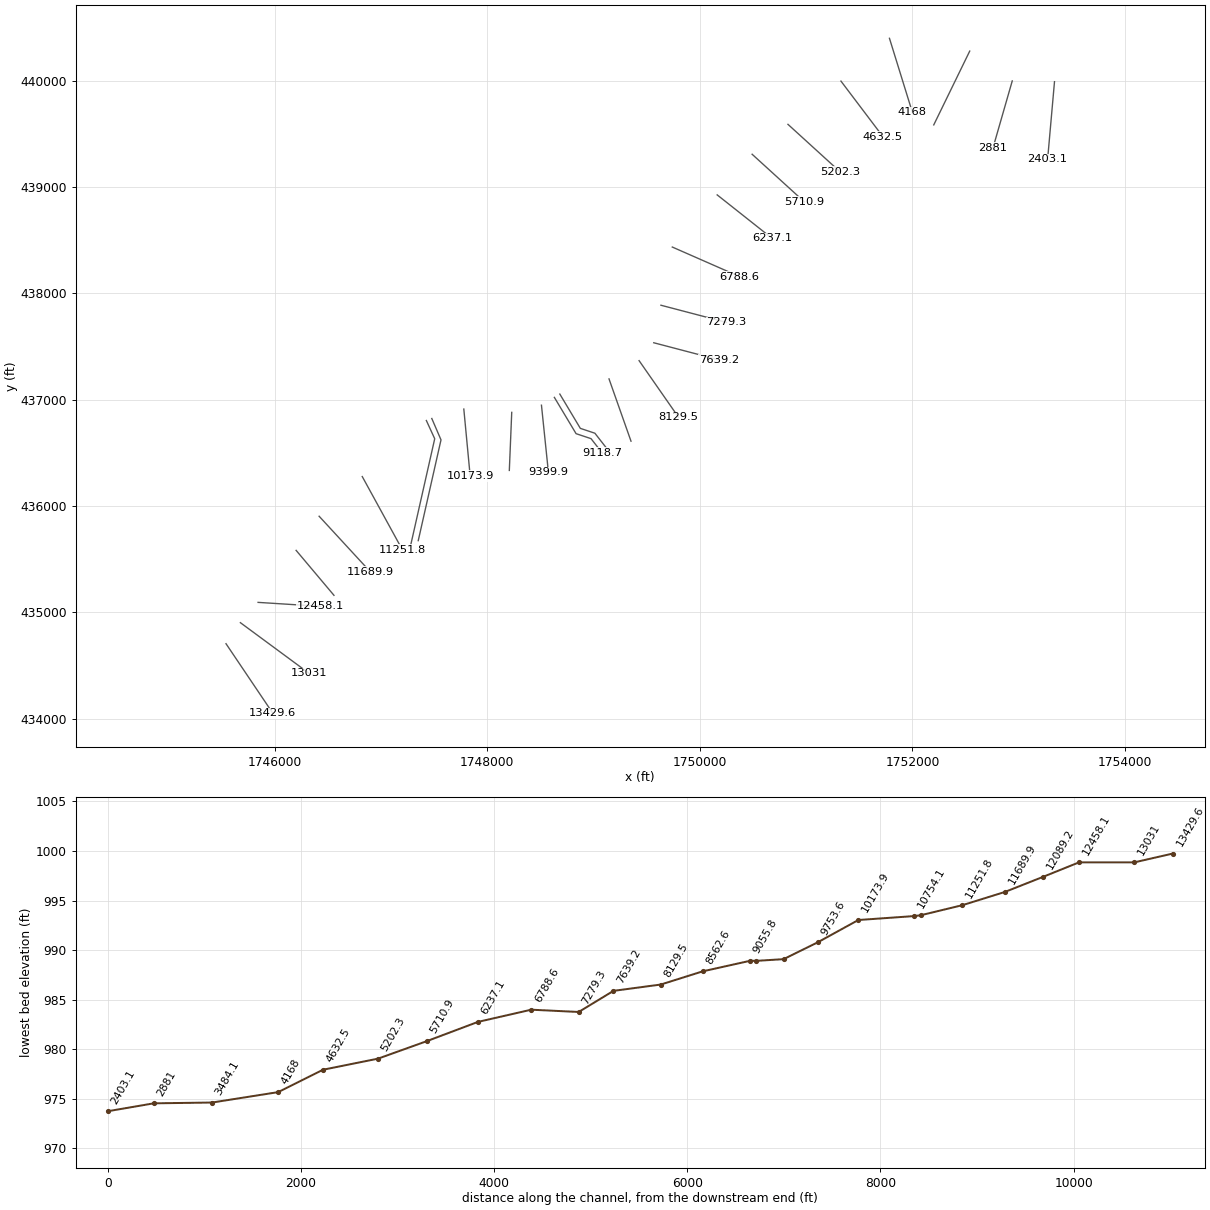
HEC-RAS study RFkMrcleRn.prj: RFkMrcleRn

--- RFkMrcleRn.g01 (geometry) --- (continued)

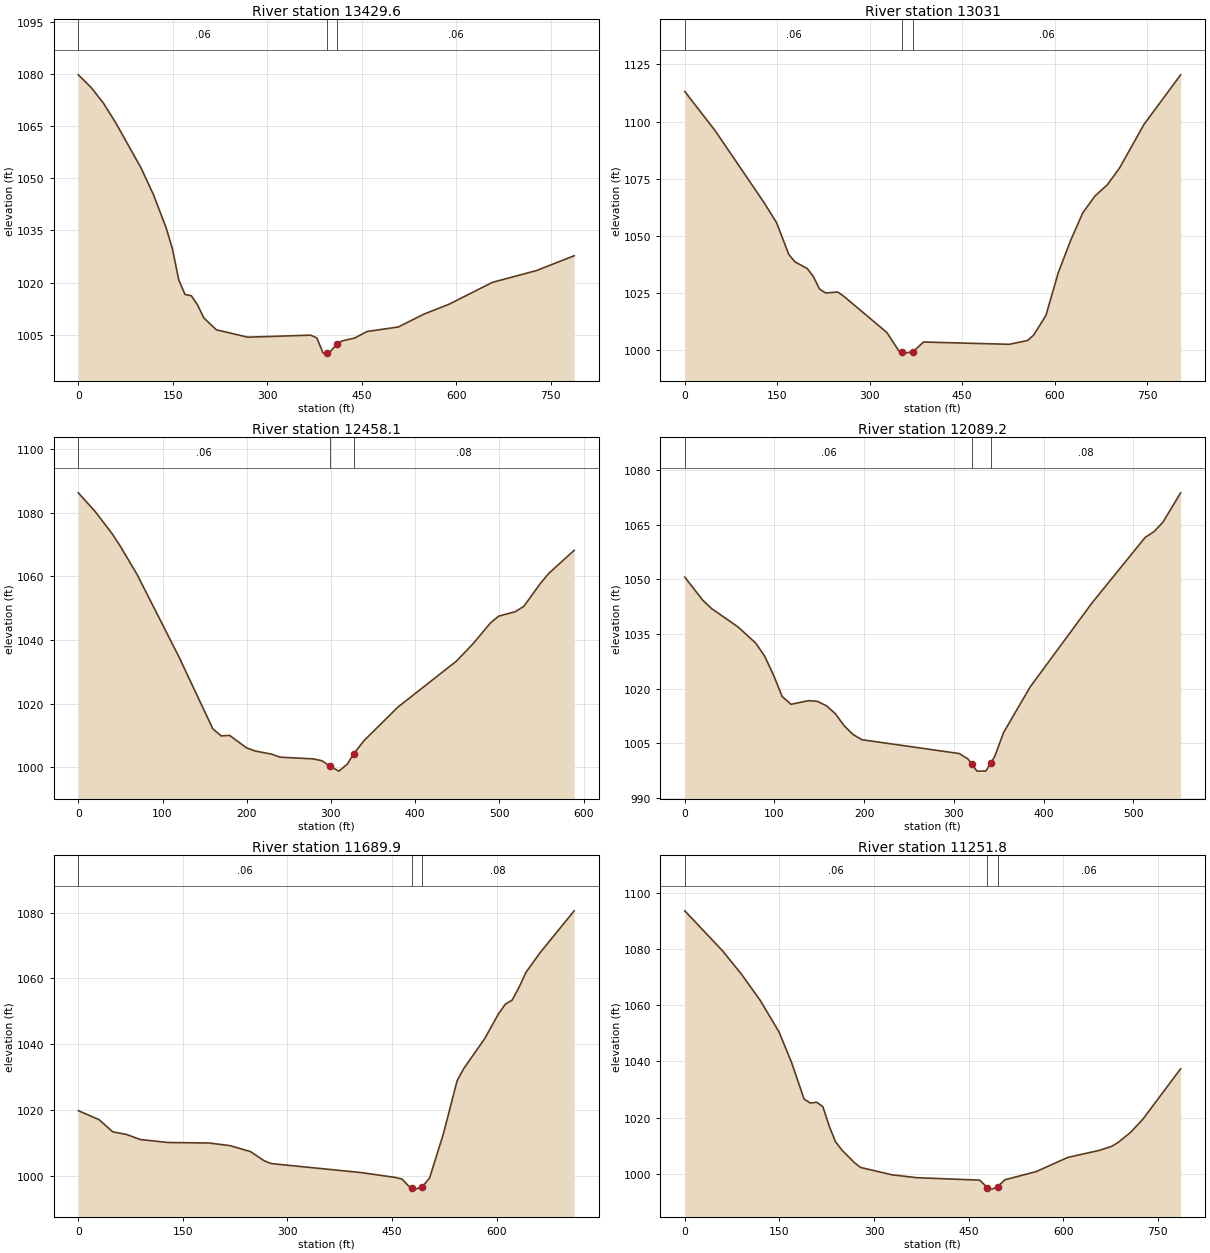
Type RM Length L Ch R = 1 ,13429.6 ,390.3,398.6,409.4
XS GIS Cut Line= 2
     1745540.948      434705.067     1745980.432      434052.475
#Sta/Elev= 30
       0 1079.72    19.9 1076.18    39.8  1071.6    59.8  1065.8    99.6 1052.94
   119.5 1045.17   139.4 1035.71   149.4 1029.68   159.4 1020.76   169.3  1016.6
   179.3 1016.24   189.2 1013.59   199.2 1009.85   219.1 1006.44   268.9 1004.32
   368.5 1004.91   378.4 1004.12   388.4  999.74   394.8  999.84   398.4  999.89
   410.1  1002.3   418.3 1003.24   438.2 1004.05   458.1 1005.96   507.9 1007.26
   547.8 1010.91   587.6 1013.74   657.3 1020.09     727 1023.47   786.8 1027.73
#Mann= 3 , 0 , 0
       0     .06       0   394.8    .045       0   410.1     .06       0
Bank Sta=394.8,410.1
XS Rating Curve= 0 ,0
Exp/Cntr=0.3,0.1

Type RM Length L Ch R = 1 ,13031   ,559.7,572.9,582.3
XS GIS Cut Line= 2
     1745676.255      434903.029     1746323.672      434425.881
#Sta/Elev= 30
       0 1113.15    49.6 1095.88   129.1 1064.39   148.9 1055.79   168.8 1041.89
   178.7 1038.72   198.6  1035.8   208.5  1032.3   218.4  1026.9   228.4 1025.14
   248.2 1025.54   258.2 1023.62   327.7 1007.87   347.5  999.71   352.9  999.24
   357.4  998.85   370.4  999.51   387.2  1003.7   526.2  1002.7     556 1004.38
     566 1006.78   585.8 1015.36   605.7 1033.95   625.5 1047.88   645.4 1060.09
   665.2 1067.47   685.1 1072.32     705 1079.66   744.7 1098.72   804.2 1120.42
#Mann= 3 , 0 , 0
       0     .06       0   352.9    .045       0   370.4     .06       0
Bank Sta=352.9,370.4
XS Rating Curve= 0 ,0
Exp/Cntr=0.3,0.1

Type RM Length L Ch R = 1 ,12458.1 ,387.1,368.9,350.6
XS GIS Cut Line= 2
     1745842.783      435094.044     1746430.456      435056.868
#Sta/Elev= 30
       0  1086.2      20 1080.33    39.9 1073.47    49.9 1069.43    69.9 1060.51
   119.8 1034.54   159.7 1012.14   169.7  1009.9   179.6 1010.07   199.6 1006.18
   209.6 1005.19   229.6 1004.18   239.5 1003.24   279.4 1002.68   289.4  1002.1
   298.6 1000.43   309.4  998.85   319.4 1001.05   326.9 1004.28   339.3 1008.42
   379.3  1018.9   449.1  1033.4   469.1 1038.93     489 1045.24     499 1047.48
     519 1048.91     529 1050.56   548.9 1057.83   558.9 1060.98   588.8 1068.15
#Mann= 3 , 0 , 0
       0     .06       0   298.6    .045       0   326.9     .08       0
Bank Sta=298.6,326.9
XS Rating Curve= 0 ,0
Exp/Cntr=0.3,0.1

Type RM Length L Ch R = 1 ,12089.2 ,398.3,399.3,400.3
XS GIS Cut Line= 2
     1746200.696      435583.239     1746556.821      435160.311
#Sta/Elev= 30
       0 1050.59    19.8 1044.33    29.6 1042.02    59.2 1036.96      79 1032.52
    88.9 1028.99    98.7 1023.87   108.6 1017.87   118.5 1015.72   138.2 1016.73
   148.1 1016.51     158  1015.3   167.8 1013.17   177.7 1009.84   187.6 1007.45
   197.5 1006.01   306.1 1002.22   315.9 1000.71   320.2  999.27   325.8   997.4
   335.7  997.42   341.1   999.6   345.6 1001.41   355.4 1007.95     385 1020.44
   454.2 1043.55   513.4 1061.49   523.3 1063.06   533.2 1065.66   552.9  1073.7
#Mann= 3 , 0 , 0
       0     .06       0   320.2    .045       0   341.1     .08       0
Bank Sta=320.2,341.1
XS Rating Curve= 0 ,0
Exp/Cntr=0.3,0.1

Type RM Length L Ch R = 1 ,11689.9 ,443.6,438.2,432.4
XS GIS Cut Line= 2
     1746417.089      435904.382     1746899.171      435381.337
#Sta/Elev= 30
       0 1019.73    29.6 1017.03    49.4  1013.3    69.2 1012.49    88.9 1010.96
   128.4 1010.05   187.7  1009.9   217.4  1009.1     247 1007.28   266.8 1004.48
   276.6 1003.64   405.1 1000.91   454.5  999.42   464.3  998.93   474.2  996.72
   478.6  996.34   484.1  995.86   493.6  996.62   503.8   999.2   523.6  1012.6
   543.4 1028.87   553.2 1032.64   582.9 1041.64   602.6 1049.15   612.5 1052.13
   622.4 1053.39   632.3 1057.32   642.2 1061.83   661.9 1067.66   711.3 1080.55
#Mann= 3 , 0 , 0
       0     .06       0   478.6    .045       0   493.6     .08       0
Bank Sta=478.6,493.6
XS Rating Curve= 0 ,0
Exp/Cntr=0.3,0.1

Type RM Length L Ch R = 1 ,11251.8 ,451.6,432.8,407.8
XS GIS Cut Line= 2
     1746823.038      436277.548     1747200.841      435588.193
#Sta/Elev= 30
       0 1093.67    59.7 1079.46    89.6 1071.17   119.4 1061.84   149.3 1050.57
   169.2  1039.7   189.1 1026.63     199  1025.2     209  1025.5   218.9 1023.91
   228.9 1017.02   238.8 1011.48   248.8 1008.51   268.7 1004.01   278.6 1002.26
   328.4  999.63   368.2   998.6   467.7  997.73   479.8  995.02   487.6  994.53
   496.3  995.44   507.5  997.86   557.2 1000.78     607 1005.81   656.7 1008.31
   676.6 1009.75   686.6 1011.09   706.5  1014.7   726.4 1019.48   786.1 1037.41
#Mann= 3 , 0 , 0
       0     .06       0   479.8    .045       0   496.3     .06       0
Bank Sta=479.8,496.3
XS Rating Curve= 0 ,0
Exp/Cntr=0.3,0.1

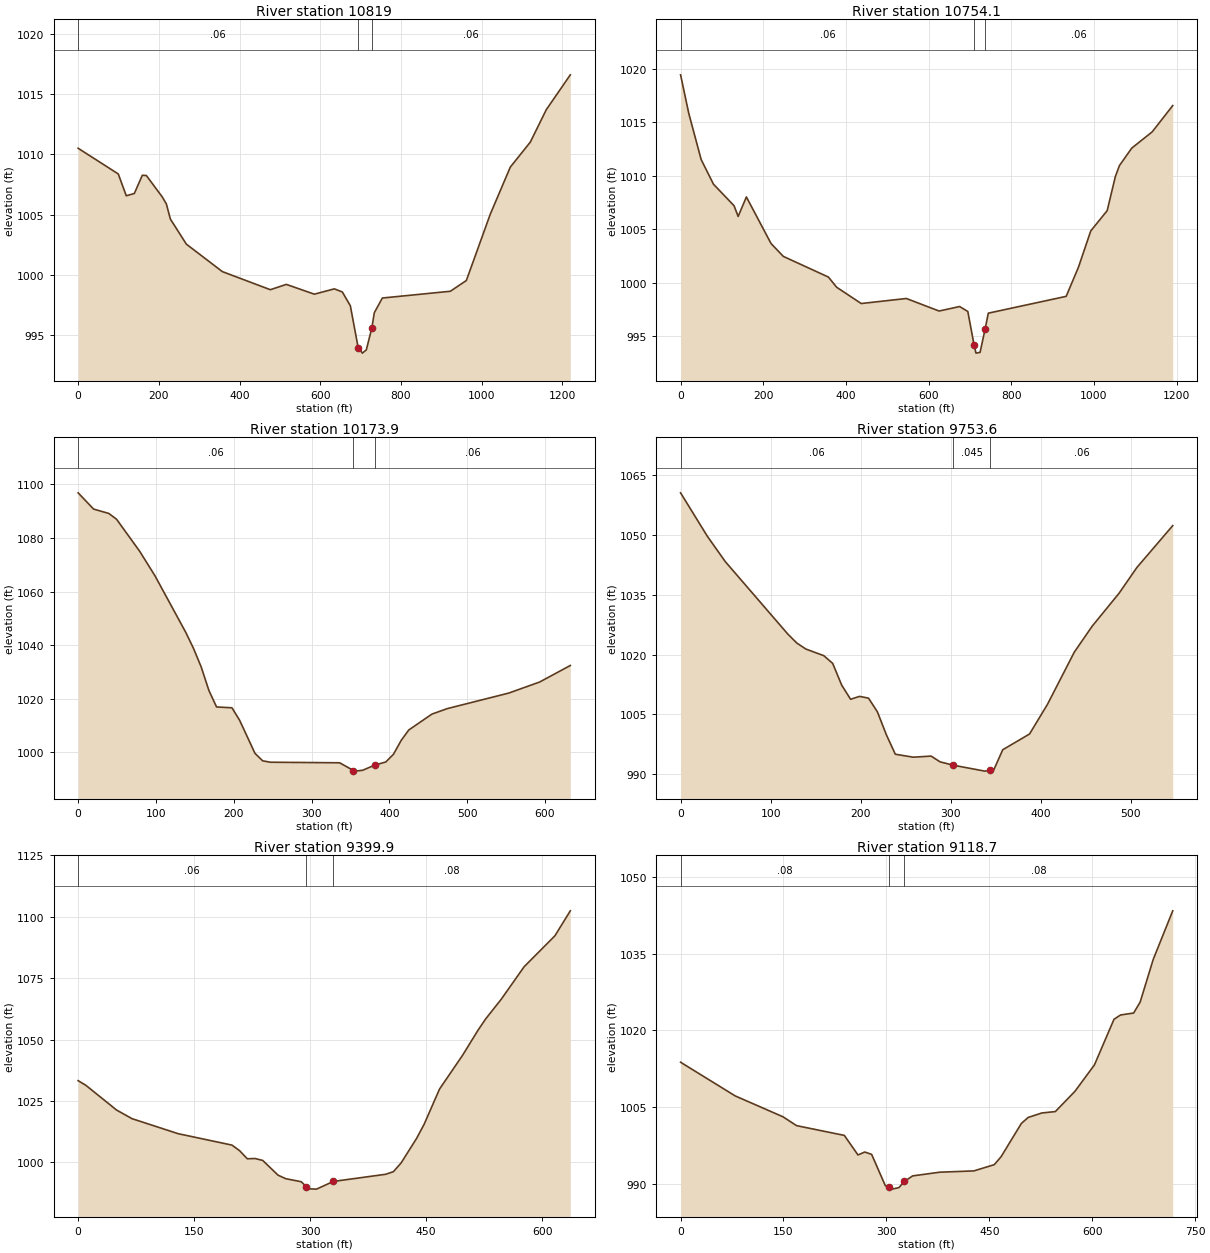
Type RM Length L Ch R = 1 ,10819   ,62.6,65,73.4
XS GIS Cut Line= 3
     1747426.084      436804.956     1747504.816      436633.287
     1747277.755      435628.093
#Sta/Elev= 30
       0  1010.5    99.4 1008.37   119.3 1006.56   139.2 1006.75     159 1008.26
     169 1008.24   208.7 1006.45   218.6 1005.88   228.5 1004.63   268.1 1002.55
   357.3 1000.27   476.2  998.77   515.8  999.21   585.2   998.4   634.8  998.84
   654.6  998.58   674.4  997.44   693.8  993.97   704.1  993.51     714  993.78
   727.7   995.6   733.8  996.86   753.7  998.08   922.1  998.64   961.8  999.53
  1021.2 1005.04  1070.8 1008.94  1120.3 1011.01  1159.9  1013.7  1219.4 1016.59
#Mann= 3 , 0 , 0
       0     .06       0   693.8    .045       0   727.7     .06       0
Bank Sta=693.8,727.7
XS Rating Curve= 0 ,0
Exp/Cntr=0.3,0.1

Type RM Length L Ch R = 1 ,10754.1 ,572.3,580.2,587
XS GIS Cut Line= 3
     1747477.413      436823.867      1747563.96      436622.802
      1747349.83      435674.859
#Sta/Elev= 30
       0 1019.41    19.9  1015.8    49.8  1011.5    79.6  1009.2   129.4 1007.19
   139.3 1006.19   159.2 1008.01   218.9 1003.66   248.6 1002.46   357.7 1000.53
   377.6  999.58   437.1  998.06   546.2  998.53   625.5  997.36   675.1  997.78
   694.9  997.32     710  994.21   714.7  993.43   724.6   993.5   736.7  995.67
   744.5  997.16   932.9  998.73   962.6 1001.45   992.4 1004.84  1032.1 1006.73
  1051.9 1009.92  1061.8 1010.94  1091.6 1012.57  1141.1 1014.09  1190.7 1016.54
#Mann= 3 , 0 , 0
       0     .06       0     710    .045       0   736.7     .06       0
Bank Sta=710,736.7
XS Rating Curve= 0 ,0
Exp/Cntr=0.3,0.1

Type RM Length L Ch R = 1 ,10173.9 ,427.1,420.2,415.7
XS GIS Cut Line= 2
     1747778.662      436912.633     1747838.422      436282.858
#Sta/Elev= 30
       0 1096.82    19.8 1090.77    39.5 1089.12    49.4 1086.96    79.1 1075.02
    98.8 1065.86   138.4 1044.74   148.3 1038.79   158.2 1031.86     168 1023.17
   177.9 1016.96   197.7 1016.65   207.6 1011.98   227.3  999.66   237.2  996.87
   247.1  996.35   336.1  996.14   353.9  993.26   355.8  993.03   365.7  993.35
   381.6  995.32   395.4  996.43   405.3  999.32   415.2 1004.48     425 1008.38
   454.7 1014.29   474.4 1016.34   553.5 1022.14   593.1 1026.25   632.6 1032.43
#Mann= 3 , 0 , 0
       0     .06       0   353.9    .045       0   381.6     .06       0
Bank Sta=353.9,381.6
XS Rating Curve= 0 ,0
Exp/Cntr=0.3,0.1

Type RM Length L Ch R = 1 ,9753.6  ,345.9,353.7,358.5
XS GIS Cut Line= 2
     1748229.538      436881.607     1748206.867      436335.286
#Sta/Elev= 30
       0 1060.63    29.8 1049.71    49.7 1043.36   119.3 1025.14   129.2 1022.92
   139.2 1021.42   159.1 1019.76     169 1017.82     179 1012.37   188.9 1008.81
   198.8 1009.54   208.8  1009.1   218.7 1005.65   228.7  999.87   238.6  995.02
   258.5  994.28   278.4  994.55   288.3  993.11   303.1  992.26     338  990.78
   343.7  990.96     348   991.1   357.9  996.14   387.7  1000.1   407.6 1007.53
   437.4 1020.63   457.3 1027.16   487.1  1035.4     507  1041.9   546.8  1052.4
#Mann= 3 , 0 , 0
       0     .06       0   303.1    .045       0   343.7     .06       0
Bank Sta=303.1,343.7
XS Rating Curve= 0 ,0
Exp/Cntr=0.3,0.1

Type RM Length L Ch R = 1 ,9399.9  ,271.3,281.3,291.1
XS GIS Cut Line= 2
     1748509.272       436948.99     1748574.896      436315.916
#Sta/Elev= 30
       0 1033.25     9.9 1031.38    49.7 1021.29    69.6 1017.78   129.3 1011.66
   198.9 1007.01   208.8 1004.74   218.8 1001.43   228.7 1001.55   238.7 1000.77
   258.6  994.75   268.5  993.33   288.4   992.1   295.1  990.13   298.3  989.19
   308.3  989.08   329.9   992.2   397.8  995.13   407.7  996.18   417.7  999.76
   437.6 1009.68   447.5 1015.52   467.4 1029.84   497.2  1043.6   517.1 1053.77
   527.1 1058.42     547 1066.33   576.8 1079.65   616.6 1092.24   636.5 1102.41
#Mann= 3 , 0 , 0
       0     .06       0   295.1    .045       0   329.9     .08       0
Bank Sta=295.1,329.9
XS Rating Curve= 0 ,0
Exp/Cntr=0.3,0.1

Type RM Length L Ch R = 1 ,9118.7  ,60.9,62.8,72.5
XS GIS Cut Line= 4
     1748630.747      437022.515     1748835.032      436681.145
     1748975.864        436634.2     1749081.195      436499.304
#Sta/Elev= 30
       0 1013.78    79.6 1007.18   149.2 1003.09   169.1 1001.35   238.7  999.44
   258.6  995.61   268.5  996.18   278.5  995.72   298.4  989.61   303.8  989.23
   308.3  988.91   318.3  989.21   326.2  990.41   338.2   991.5   377.9  992.23
   427.5  992.48   457.2   993.7   467.1  995.24   496.8 1001.79   506.7 1002.96
   526.5 1003.83   546.3 1004.11   574.8 1008.07   603.3 1013.26   631.8  1022.2
   641.4 1023.04   660.4 1023.42   669.9 1025.56   688.9 1033.91   717.4 1043.45
#Mann= 3 , 0 , 0
       0     .08       0   303.8    .045       0   326.2     .08       0
Bank Sta=303.8,326.2
XS Rating Curve= 0 ,0
Exp/Cntr=0.3,0.1

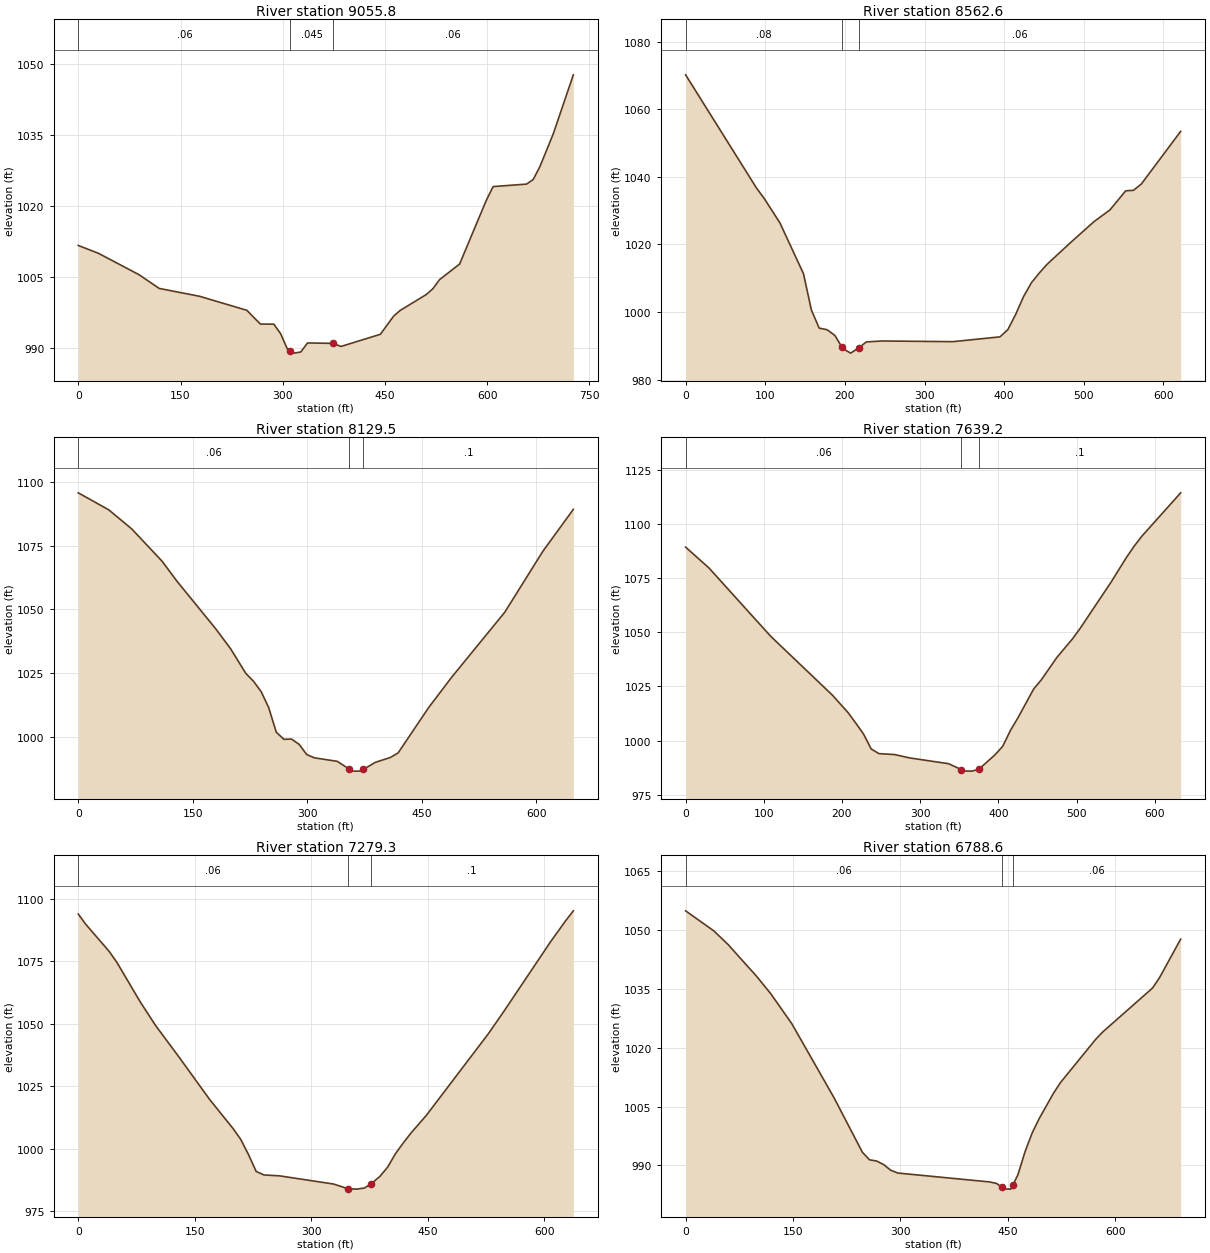
Type RM Length L Ch R = 1 ,9055.8  ,499.3,493.2,477.9
XS GIS Cut Line= 4
     1748682.078      437053.583       1748875.1      436731.034
     1749012.014      436685.396     1749138.864      436522.939
#Sta/Elev= 30
       0 1011.65    29.7 1009.99      89 1005.49   118.7 1002.58     178 1000.92
   247.3  997.96   267.1  995.06   286.9  995.03   296.8  993.04   306.6  989.84
   311.2  989.41   316.5  988.92   326.4  989.16   336.3  991.07   373.6  990.98
   385.5  990.33   443.2   992.9   462.5   996.7   472.1  997.92   510.6  1001.3
   520.2 1002.51     530 1004.43   559.5 1007.74   598.7 1021.21   608.6 1024.08
   657.6 1024.61   667.4 1025.58   677.2 1028.28   696.9 1035.23   726.3 1047.68
#Mann= 3 , 0 , 0
       0     .06       0   311.2    .045       0   373.6     .06       0
Bank Sta=311.2,373.6
XS Rating Curve= 0 ,0
Exp/Cntr=0.3,0.1

Type RM Length L Ch R = 1 ,8562.6  ,425.3,433.2,437.6
XS GIS Cut Line= 2
     1749144.958      437196.428     1749351.985      436610.284
#Sta/Elev= 30
       0 1070.16    88.8 1036.75    98.7 1033.58   118.4 1026.38     148 1011.34
   157.9 1000.62   167.7  995.24   177.6  994.78   187.5  993.07   195.8   989.8
   197.3  989.21   207.2  987.85   217.6  989.44   226.9  991.16   246.7  991.44
   335.5  991.24   394.7  992.66   404.6   994.8   414.4  999.29   424.3 1004.56
   434.2 1008.67     444 1011.52   453.9 1014.13   483.5 1020.58   513.1  1026.8
   532.8 1030.21   552.6 1035.86   562.4 1036.01   572.3 1037.89   621.6 1053.44
#Mann= 3 , 0 , 0
       0     .08       0   195.8    .045       0   217.6     .06       0
Bank Sta=195.8,217.6
XS Rating Curve= 0 ,0
Exp/Cntr=0.3,0.1

Type RM Length L Ch R = 1 ,8129.5  ,474.3,490.2,506.3
XS GIS Cut Line= 2
     1749427.973      437368.132     1749798.868      436835.824
#Sta/Elev= 30
       0 1095.73    39.9 1089.06    69.9 1081.61   109.8 1068.91   129.8 1060.87
   179.7 1042.53   199.6 1034.55   219.6 1024.86   229.6 1021.79   239.6 1017.76
   249.5 1011.49   259.5 1001.79   269.5     999   279.5   999.1   289.5  997.02
   299.4  993.02   309.4  991.74   339.4  990.36   354.7  987.39   359.3  986.52
   369.3  986.52   373.6   987.2   389.3  989.96   409.2   991.9   419.2  993.68
   459.1 1011.42   489.1 1023.27     559  1048.9   608.8 1072.76   648.8 1089.25
#Mann= 3 , 0 , 0
       0     .06       0   354.7    .045       0   373.6      .1       0
Bank Sta=354.7,373.6
XS Rating Curve= 0 ,0
Exp/Cntr=0.3,0.1

Type RM Length L Ch R = 1 ,7639.2  ,359.9,359.9,359.9
XS GIS Cut Line= 2
     1749566.038      437536.433     1750178.519      437375.902
#Sta/Elev= 30
       0 1089.33    29.7 1079.78   108.8 1048.17     188 1020.88   207.8 1012.89
   217.6  1008.1   227.6 1002.98   237.4   996.1   247.3  993.96   267.1  993.54
   286.9  991.96   336.4  989.31   352.8  986.59   356.2  985.94     366  985.88
   374.9  986.69   395.7  993.42   405.6  997.35   415.5 1004.69   425.4 1010.71
   445.2 1023.82   455.1 1028.11   474.9 1038.41   494.7 1046.91   504.6  1051.8
   544.1 1073.12   563.9 1084.61   573.8  1089.8   583.7 1094.44   633.2 1114.42
#Mann= 3 , 0 , 0
       0     .06       0   352.8    .045       0   374.9      .1       0
Bank Sta=352.8,374.9
XS Rating Curve= 0 ,0
Exp/Cntr=0.3,0.1

Type RM Length L Ch R = 1 ,7279.3  ,494.2,490.7,487.1
XS GIS Cut Line= 2
      1749633.63      437889.409     1750250.098      437727.832
#Sta/Elev= 30
       0 1093.83      10 1089.61    39.8 1078.89    49.8 1074.44    79.7 1058.72
    99.6 1049.19   129.4 1036.72   169.3 1019.55   199.2 1008.02   209.1 1003.67
   219.1  997.59     229  990.83     239  989.42   258.9  989.07   328.6  985.79
     347  983.92   358.5  983.75   368.4   984.2   376.5  985.76   388.4  988.88
   398.3  992.57   408.3  997.92   418.2 1002.17   428.2 1006.16   448.1 1013.28
   527.8  1045.9   547.7 1054.81   607.4 1082.48   627.3 1091.12   637.3 1095.13
#Mann= 3 , 0 , 0
       0     .06       0     347    .045       0   376.5      .1       0
Bank Sta=347,376.5
XS Rating Curve= 0 ,0
Exp/Cntr=0.3,0.1

Type RM Length L Ch R = 1 ,6788.6  ,557.4,551.5,545.5
XS GIS Cut Line= 2
     1749740.504      438436.765     1750373.723      438158.722
#Sta/Elev= 30
       0 1054.86    39.5 1049.74    59.3 1046.28    98.8 1038.26   118.6 1033.83
   148.2 1026.16   207.5  1007.2     247  993.36   256.9  991.45   266.8  991.14
   276.6  990.24   286.5   988.8   296.4  988.08   424.8  985.81   434.7  985.41
   442.1   984.4   444.6  984.06   454.5  983.98   457.1  984.96   464.3  987.67
   474.2  993.52   484.1  998.26     494 1001.96   513.7 1008.32   523.6  1011.1
     573 1022.16   582.9 1024.04   652.1 1035.16   661.9 1037.78   691.6 1047.65
#Mann= 3 , 0 , 0
       0     .06       0   442.1    .045       0   457.1     .06       0
Bank Sta=442.1,457.1
XS Rating Curve= 0 ,0
Exp/Cntr=0.3,0.1

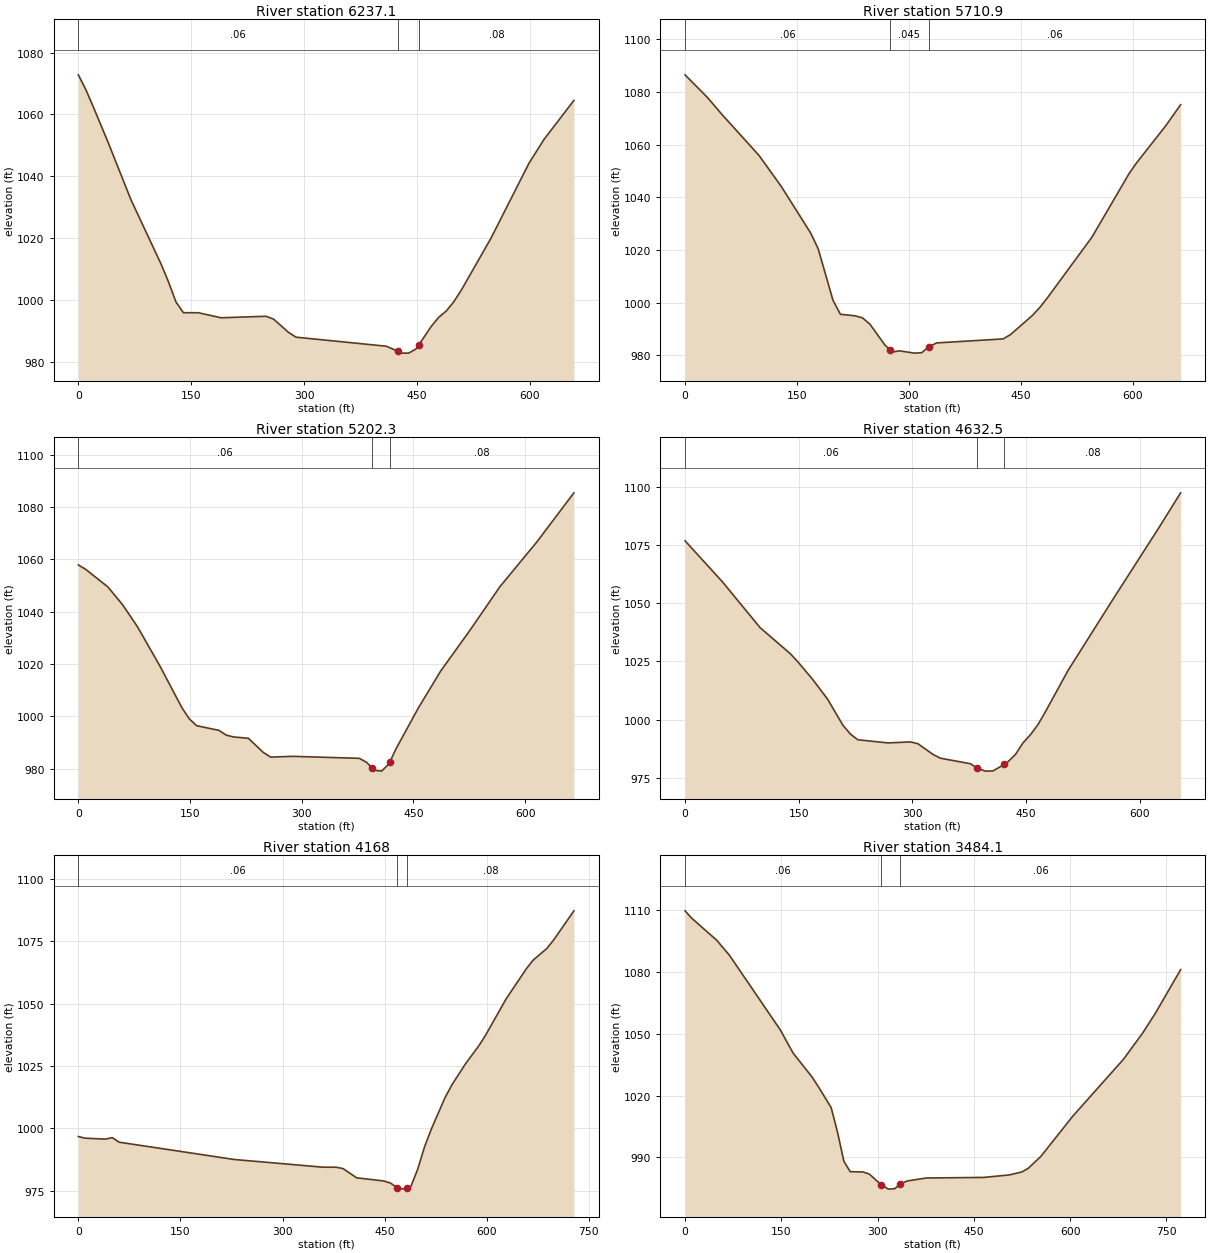
Type RM Length L Ch R = 1 ,6237.1  ,534,526.2,515.3
XS GIS Cut Line= 2
     1750162.749      438927.482     1750679.297      438518.781
#Sta/Elev= 30
       0 1072.82      10 1068.02      20  1062.4    39.9 1050.78    69.9 1032.42
   109.8 1011.68   119.8 1005.85   129.7  999.35   139.7  995.83   159.7  995.82
   189.6  994.19   249.5  994.68   259.5  993.76   279.4  989.47   289.4  987.91
   409.2  984.99   424.9  983.34   429.1  982.75   439.1  982.75   449.1  984.14
   452.8  985.49   469.1  991.41     479  994.34     489  996.36     499  999.36
     509 1003.11   548.9 1020.13   598.8 1044.11   618.8 1051.86   658.7 1064.54
#Mann= 3 , 0 , 0
       0     .06       0   424.9    .045       0   452.8     .08       0
Bank Sta=424.9,452.8
XS Rating Curve= 0 ,0
Exp/Cntr=0.3,0.1

Type RM Length L Ch R = 1 ,5710.9  ,501.8,508.6,517.9
XS GIS Cut Line= 2
     1750491.646      439309.714     1750982.963       438862.29
#Sta/Elev= 30
       0 1086.54    29.8 1078.01    49.6 1071.45    99.2 1055.91   128.9 1044.19
   168.6 1026.36   178.5 1020.47   198.4 1000.87   208.3  995.58   228.1  994.99
     238   994.2     248  991.78   267.8  983.98   274.5  982.14   277.7  981.26
   287.6  981.68   307.5  980.82   317.4     981   326.6  983.15   337.2  984.69
   426.5  986.22   436.4  987.86   466.2  995.25   476.1  998.31     486 1001.88
   545.5 1024.84   595.1 1048.88     605 1052.94   644.7 1067.24   664.5 1075.19
#Mann= 3 , 0 , 0
       0     .06       0   274.5    .045       0   326.6     .06       0
Bank Sta=274.5,326.6
XS Rating Curve= 0 ,0
Exp/Cntr=0.3,0.1

Type RM Length L Ch R = 1 ,5202.3  ,573.8,569.8,565.4
XS GIS Cut Line= 2
     1750828.981      439590.982     1751320.954       439142.96
#Sta/Elev= 30
       0 1057.86     9.9 1056.17    39.7 1049.45    59.6 1042.59    79.4 1034.24
   109.2  1019.4     139 1003.33     149  999.03   158.9   996.4   188.7  994.63
   198.6  992.81   208.6   992.1   228.4  991.59   248.3  986.19   258.2   984.4
     288  984.69   377.4  983.93   387.3  982.35   394.6   980.2   397.3   979.4
   407.2  979.04   417.1  981.83   418.5  982.68     427  987.82   456.8  1003.3
   486.6 1017.33   526.4  1033.1   566.1 1049.55   615.8  1066.7   665.4 1085.42
#Mann= 3 , 0 , 0
       0     .06       0   394.6    .045       0   418.5     .08       0
Bank Sta=394.6,418.5
XS Rating Curve= 0 ,0
Exp/Cntr=0.3,0.1

Type RM Length L Ch R = 1 ,4632.5  ,472.2,464.5,456.2
XS GIS Cut Line= 2
     1751327.452      439997.898     1751722.102      439476.077
#Sta/Elev= 30
       0 1076.77    49.6 1059.06    99.1 1039.49   138.8 1028.35   148.7  1024.9
   168.5 1017.27   188.4 1008.68   208.2  997.72   218.1  993.89     228  991.38
   267.6  990.03   297.4  990.45   307.3  989.71   327.1  985.12     337  983.48
   376.7  981.09   385.8  979.15   396.5  977.92   406.4  977.99   421.5  980.81
   426.2  981.89   436.2   985.1   446.1  990.03     456  993.56   465.9   997.9
   475.8 1003.46   505.6 1021.14     565 1051.71   624.5 1081.86   654.2 1097.35
#Mann= 3 , 0 , 0
       0     .06       0   385.8    .045       0   421.5     .08       0
Bank Sta=385.8,421.5
XS Rating Curve= 0 ,0
Exp/Cntr=0.3,0.1

Type RM Length L Ch R = 1 ,4168    ,699.7,684,667.5
XS GIS Cut Line= 2
      1751784.01      440400.376     1751999.397      439704.942
#Sta/Elev= 30
       0  996.74      10  996.08    39.9  995.71    49.9  996.31    59.8  994.48
   229.4  987.53     359  984.46     379  984.44   388.9  983.89   408.9  980.19
   448.8  978.92   458.8  978.07   468.2  976.21   478.7  975.66   483.3  976.21
   488.7  976.86   498.6  983.68   508.6  992.62   518.6  999.75   538.5 1012.22
   548.5 1017.33   568.5  1025.8   588.4 1033.14   598.4 1037.42   628.3 1051.86
   658.2 1064.02   668.2 1067.47   688.1 1072.09   698.1 1075.47     728 1087.22
#Mann= 3 , 0 , 0
       0     .06       0   468.2    .045       0   483.3     .08       0
Bank Sta=468.2,483.3
XS Rating Curve= 0 ,0
Exp/Cntr=0.3,0.1

Type RM Length L Ch R = 1 ,3484.1  ,599.3,603,605.9
XS GIS Cut Line= 2
     1752539.239      440280.212     1752200.898      439586.108
#Sta/Elev= 30
       0 1109.72     9.9 1106.27    49.5  1095.4    69.3 1088.09   148.5 1051.89
   168.3 1040.69     198 1028.99   207.9 1024.25   227.7 1014.17   237.6 1002.23
   247.5  988.08   257.4  983.08   277.2  982.95   287.1  981.93   305.5  976.76
   316.8  974.61   326.7  974.82   335.6  977.18   346.5   978.6   376.2  980.02
   465.3  980.29   504.9  981.49   524.7  982.95   534.6  984.67   554.4   990.5
   603.9 1009.93   683.1 1037.64   712.8 1050.28   732.6 1059.86   772.2 1081.17
#Mann= 3 , 0 , 0
       0     .06       0   305.5    .045       0   335.6     .06       0
Bank Sta=305.5,335.6
XS Rating Curve= 0 ,0
Exp/Cntr=0.3,0.1

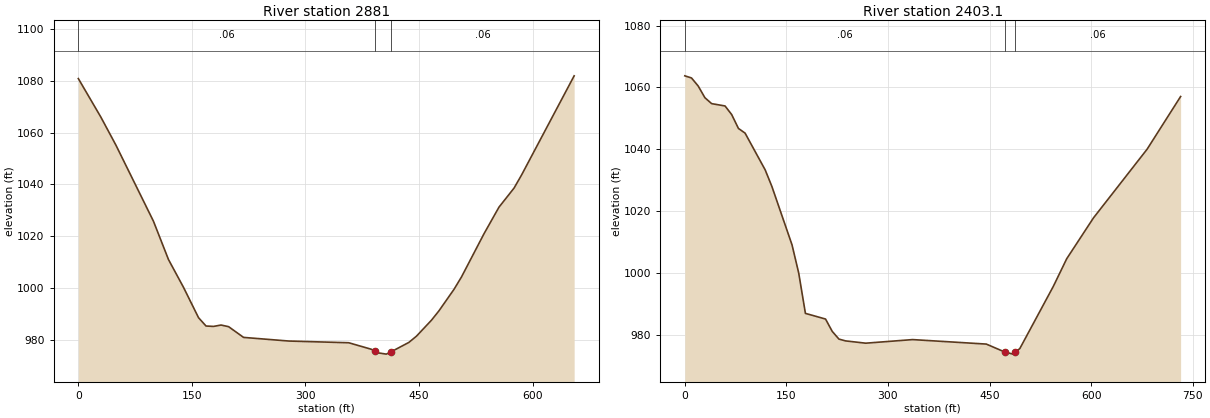
Type RM Length L Ch R = 1 ,2881    ,473.3,477.9,482.2
XS GIS Cut Line= 2
     1752939.475      439999.804      1752758.34      439370.404
#Sta/Elev= 30
       0 1080.81    29.8 1065.93    49.6 1055.17    99.2 1025.82   119.1 1011.01
   138.9 1000.31   158.8  988.58   168.7  985.37   178.6  985.22   188.5  985.75
   198.5  985.12   218.3  980.98   277.9  979.58   357.2  978.92     387  976.41
   392.2  975.66   396.9  974.98   406.9  974.53     413   975.4   436.6  979.04
   446.6  981.43   466.4  987.58   476.3  991.19   496.2  999.49   506.1 1004.26
   535.9 1020.96   555.7 1031.22   575.6 1038.57   585.5 1043.61     655 1081.87
#Mann= 3 , 0 , 0
       0     .06       0   392.2    .045       0     413     .06       0
Bank Sta=392.2,413
XS Rating Curve= 0 ,0
Exp/Cntr=0.3,0.1

Type RM Length L Ch R = 1 ,2403.1  ,440.6,445.2,449.6
XS GIS Cut Line= 2
     1753336.982      439992.577      1753272.27      439263.327
#Sta/Elev= 30
       0 1063.75     9.9 1063.06    19.8 1060.45    29.7 1056.67    39.6 1054.76
    59.4    1054    69.2 1051.23    79.2 1046.73      89 1045.22   118.7 1033.32
   128.6 1027.96   158.3  1009.1   168.2  999.96   178.1  986.91   207.8  985.08
   217.7  981.09   227.6  978.59   237.4  978.01   267.1  977.27   336.4  978.43
   445.2  976.98   472.8  974.38   484.8  973.73   488.2  974.35   494.7  975.54
   544.1  995.63   563.9 1004.58   603.5 1017.82   682.6 1040.01   732.1 1057.06
#Mann= 3 , 0 , 0
       0     .06       0   472.8    .045       0   488.2     .06       0
Bank Sta=472.8,488.2
XS Rating Curve= 0 ,0
Exp/Cntr=0.3,0.1