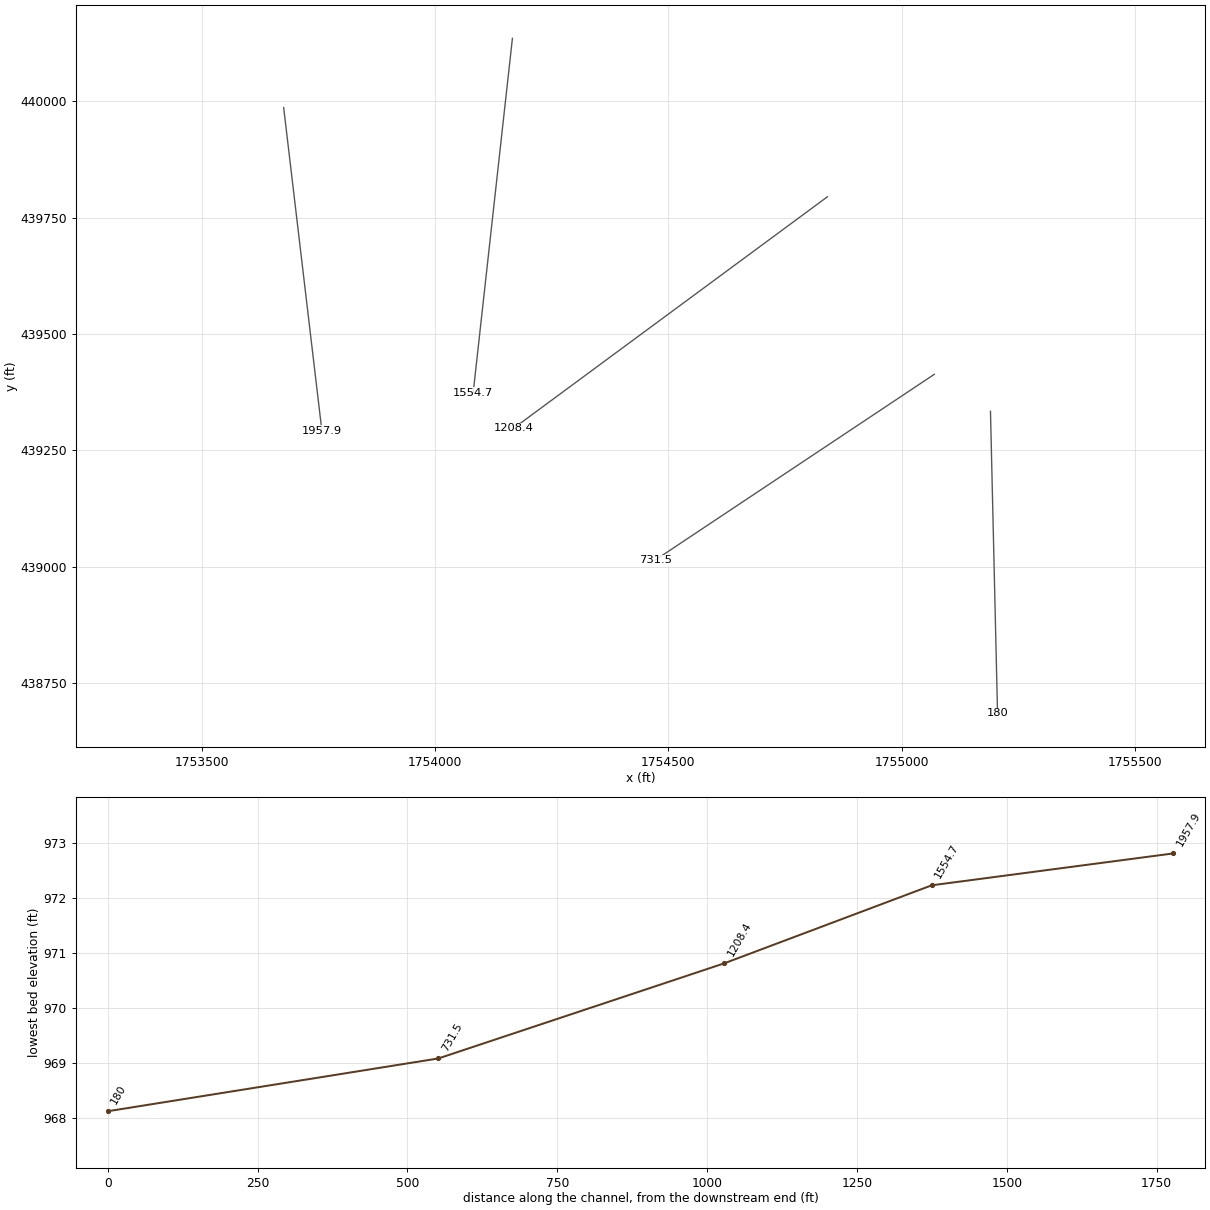
HEC-RAS study RFkMrcleRn.prj: RFkMrcleRn

--- RFkMrcleRn.g01 (geometry) --- (continued)

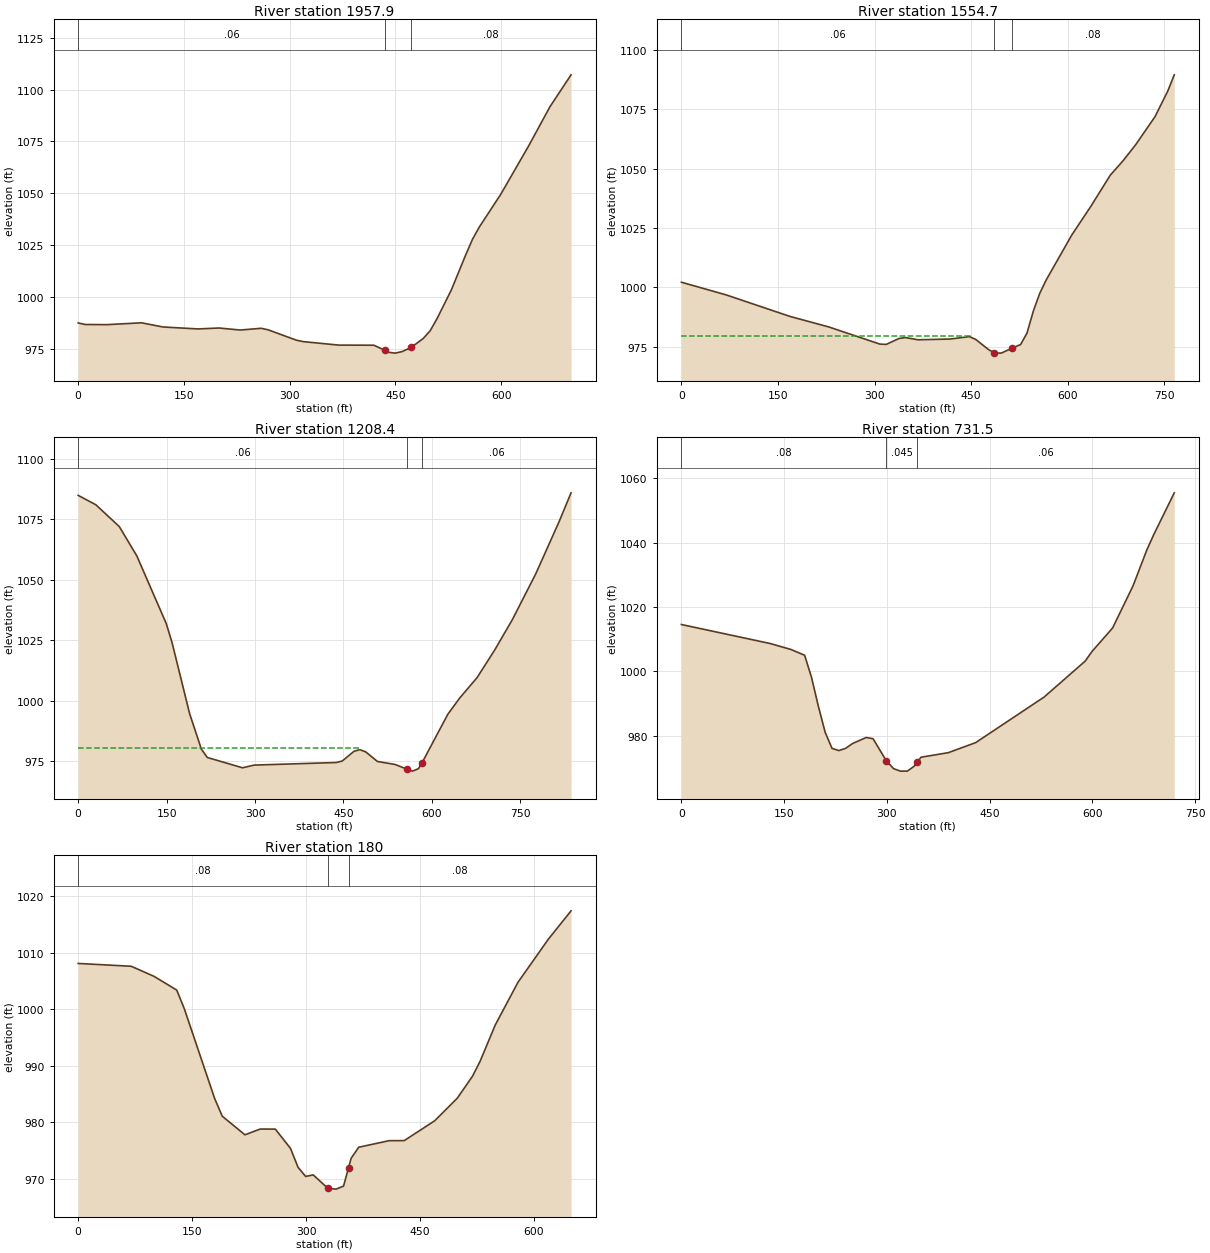
Type RM Length L Ch R = 1 ,1957.9  ,408.3,403.2,397.9
XS GIS Cut Line= 2
     1753675.787      439986.416     1753757.725      439292.043
#Sta/Elev= 30
       0  987.38      10  986.63      40  986.54    89.9  987.44   119.9  985.44
   169.8  984.48   199.8  984.93   229.7  983.95   259.7  984.79   269.7  984.03
   309.6  979.05   319.6  978.35   369.6  976.68   419.5  976.63     435  974.17
   439.5  973.27   449.5  972.81   459.5  973.55   472.5   975.6   489.4  979.84
   499.4  983.63   509.4  989.66   529.4 1003.32   549.4 1019.91   559.4 1027.76
   569.3 1033.78   599.3 1049.34   639.3 1072.94   669.2 1091.65   699.2 1107.08
#Mann= 3 , 0 , 0
       0     .06       0     435    .045       0   472.5     .08       0
Bank Sta=435,472.5
XS Rating Curve= 0 ,0
Exp/Cntr=0.3,0.1

Type RM Length L Ch R = 1 ,1554.7  ,365.6,346.3,327.3
XS GIS Cut Line= 2
     1754165.998      440135.088     1754081.938      439374.216
#Sta/Elev= 30
       0  1002.1    69.6  996.76     169  987.66   228.7  983.28   308.2  976.04
   318.1   975.9     338  978.41     348  978.78   367.8  977.85   417.6  978.17
   447.4  979.19   457.3  977.96   477.2  973.69   485.6  972.45   487.1  972.23
   497.1  972.27   512.8  974.23   526.9  975.87   536.8  980.69   546.8  990.12
   556.7   997.5   566.7 1003.12   606.4 1022.03   636.3 1034.23   666.1  1047.2
     686 1053.29   705.8 1060.13   735.7  1071.9   755.6 1082.78   765.5 1089.48
#Mann= 3 , 0 , 0
       0     .06       0   485.6    .045       0   512.8     .08       0
#XS Ineff= 2 , 0
          447.64  979.57
Permanent Ineff=
       F       F
Bank Sta=485.6,512.8
XS Rating Curve= 0 ,0
Exp/Cntr=0.3,0.1

Type RM Length L Ch R = 1 ,1208.4  ,477.8,476.9,474.2
XS GIS Cut Line= 2
     1754840.913      439794.755      1754168.65      439297.739
#Sta/Elev= 30
       0 1084.89    29.9 1081.01    69.7    1072    99.5 1059.83   149.3 1031.91
   159.2    1024   189.1  994.52     209  979.89     219  976.46   278.7  972.19
   298.6  973.31   437.9  974.37   447.9     975   467.8  979.01   477.7  979.69
   487.7  978.78   507.6  974.81   537.4  973.57   558.4  971.56   567.3  970.81
   577.3  971.85   583.4  974.33     627  994.34   646.9 1000.98   676.8 1009.57
   706.6 1020.97   736.5  1033.5   776.3 1052.52   816.1 1074.22     836 1085.94
#Mann= 3 , 0 , 0
       0     .06       0   558.4    .045       0   583.4     .06       0
#XS Ineff= 2 , 0
          478.44  980.32
Permanent Ineff=
       F       F
Bank Sta=558.4,583.4
XS Rating Curve= 0 ,0
Exp/Cntr=0.3,0.1

Type RM Length L Ch R = 1 ,731.5   ,529.1,551.5,572.8
XS GIS Cut Line= 2
     1755070.198      439413.626     1754471.604       439014.33
#Sta/Elev= 30
       0 1014.56   129.9 1008.65   159.9 1006.82   179.9 1005.02   189.9  998.23
   199.9  989.26   209.9  981.12   219.9  976.14   229.9  975.46   239.8  976.15
   249.8  977.63   269.8  979.51   279.8  979.14     299  972.35   309.8  969.85
   319.8  969.08   329.8  969.08   339.8  970.58   344.4  971.87   349.8  973.39
   389.8  974.81   429.7  977.93   529.7  992.08   589.6 1003.22   599.6 1006.22
   629.6  1013.5   659.6 1026.65   679.6 1037.73   689.6 1042.42   719.6 1055.41
#Mann= 3 , 0 , 0
       0     .08       0     299    .045       0   344.4     .06       0
#XS Ineff= 2 , 0
          277.62  978.82
Permanent Ineff=
       F       F
Bank Sta=299,344.4
XS Rating Curve= 0 ,0
Exp/Cntr=0.3,0.1

Type RM Length L Ch R = 1 ,180     ,176.9,180,184.6
XS GIS Cut Line= 2
     1755190.453      439334.235       1755205.6      438685.435
#Sta/Elev= 30
       0 1008.09    69.9 1007.59    99.8 1005.81   129.8 1003.37   139.8 1000.05
   179.7  984.17   189.7  981.04   219.6  977.74   239.6  978.76   259.6  978.75
   279.6  975.33   289.5  971.99   299.5  970.37   309.5  970.64   328.8  968.27
   339.5  968.12   349.4  968.65   356.1  971.95   359.4  973.58   369.4  975.54
   409.4   976.7   429.3  976.71   469.3  980.21   499.2  984.23   519.2  988.11
   529.2  990.75   549.1  997.17   579.1 1004.75     619 1012.37     649 1017.41
#Mann= 3 , 0 , 0
       0     .08       0   328.8    .045       0   356.1     .08       0
Bank Sta=328.8,356.1
XS Rating Curve= 0 ,0
Exp/Cntr=0.3,0.1

Chan Stop Cuts=-1
Use User Specified Reach Order=0
Composite Channel Slope=5